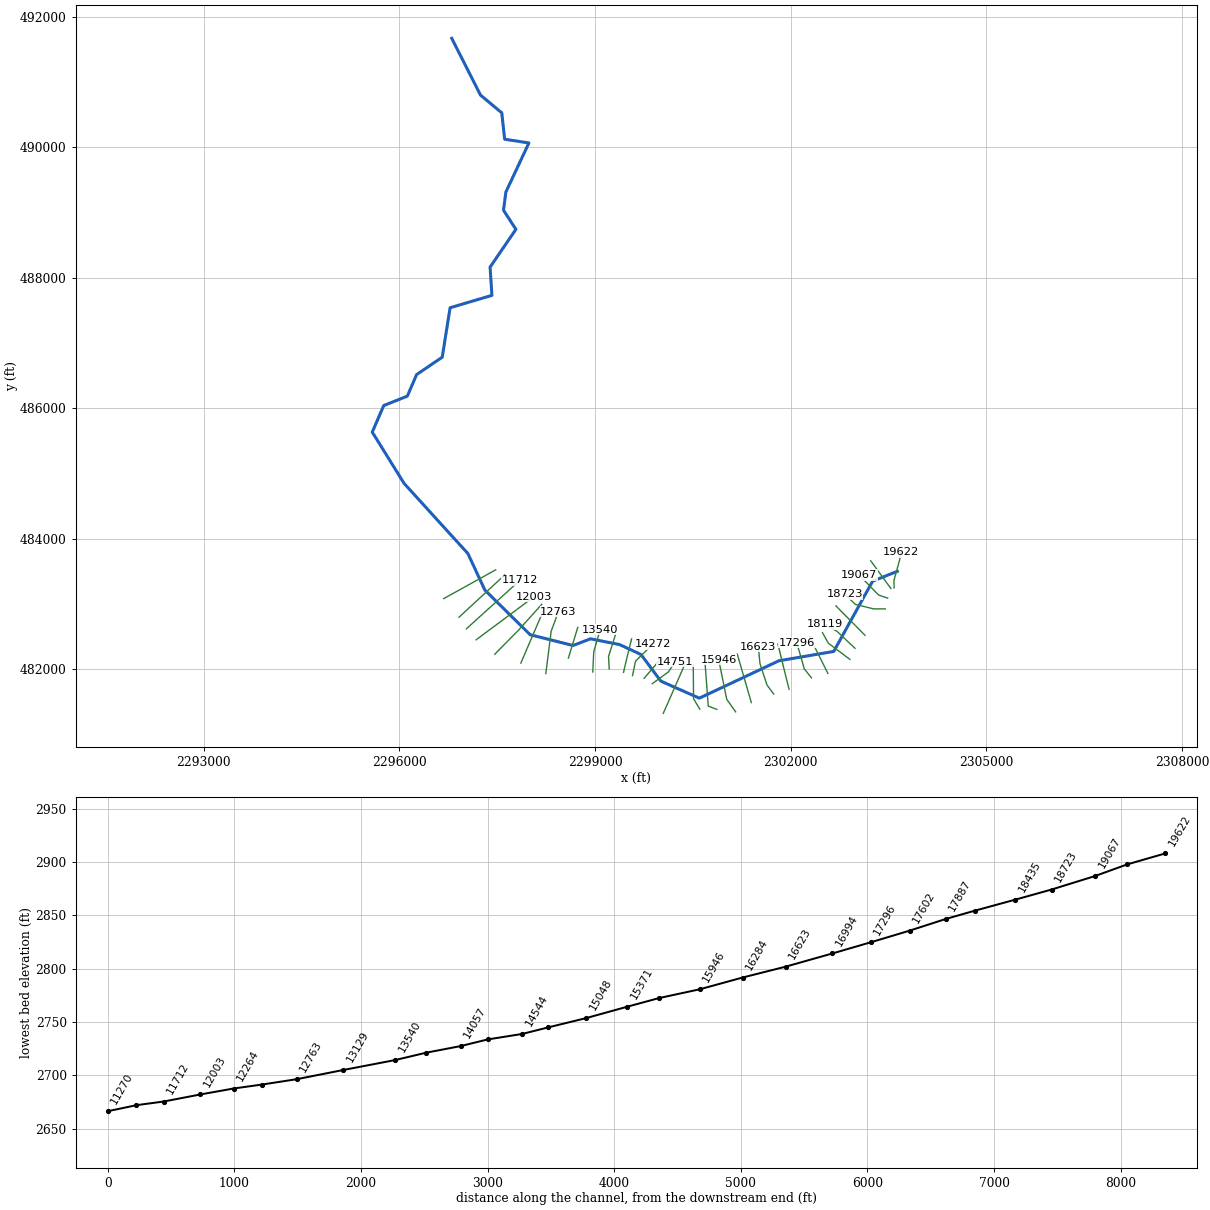
--- SHOCKRN.prj (project) ---

Proj Title=SHOCKRN
Current Plan=p01
Default Exp/Contr=0,0
English Units
Geom File=g01
Flow File=f01
Plan File=p01
Background Map Layer=Inundation Boundary (01pct Value_0)
Background Map Layer=Inundation Boundary (01pct Value_0)
Background Map Layer=Inundation Boundary (10pct Value_0)
Background Map Layer=Inundation Boundary (01pct Value_0)
BEGIN DESCRIPTION:
----------MODEL BY WOOD PLC 2021----------
Stream Name: Shock Run
Flood Zone: Approximate
Pocahontas County, WV
HEC-RAS Version: RAS 6.1
Vertical Datum: NAVD88
Projection: NAD 1983 StatePlane West Virginia S FIPS 4702 (US Feet)
Terrain: 1-meter LIDAR (FEMA Region III 3DEP collected 2016-2018)
Land Use: 2019 NLCD
Hydrologic Method:
WV SIR2010-5033 regression equations
Model Notes:
END DESCRIPTION:
DSS Export Rating Curves= 0
DSS Export Rating Curve Sorted= 0
DSS Export Volume Flow Curves= 0
DXF OffsetX= 0
DXF OffsetY= 0
DXF ScaleX= 0
DXF ScaleY= 0

--- SHOCKRN.p01 (plan) ---

Plan Title=Floodplain
Program Version=6.10
Short Identifier=Floodplain
Geom File=g01
Flow File=f01
Subcritical Flow
K Sum by GR= 0
Std Step Tol= 0.01
Critical Tol= 0.01
Num of Std Step Trials= 20
Max Error Tol= 0.3
Flow Tol Ratio= 0.001
Split Flow NTrial= 30
Split Flow Tol= 0.02
Split Flow Ratio= 0.02
Log Output Level= 0
Friction Slope Method= 1
Unsteady Friction Slope Method= 2
Unsteady Bridges Friction Slope Method= 1
Parabolic Critical Depth
Global Vel Dist= 0 , 0 , 0
Global Log Level= 0
CheckData=True
Encroach Param=-1 ,0,0, 0
Mapping Interval=1HOUR
Computation Time Step Use Courant=        0
Computation Time Step Use Time Series=    0
Computation Time Step Count To Double=0
Computation Time Step Max Doubling=0
Computation Time Step Max Halving=0
Computation Time Step Residence Courant=0
Run HTab= 0
Run UNet= 0
Run Sediment= 0
Run PostProcess= 0
Run WQNet= 0
Run RASMapper=-1
UNET Theta= 0
UNET Theta Warmup= 0
UNET ZTol= 0
UNET ZSATol= 0
UNET MxIter= 0
UNET Max Iter WO Improvement= 0
UNET MaxInSteps= 0
UNET DtIC= 0
UNET DtMin= 0
UNET MaxCRTS= 0
UNET WFStab= 0
UNET SFStab= 0
UNET WFX= 1
UNET SFX= 1
UNET Gravity=32.174
UNET 1D Methodology=Finite Difference
UNET DSS MLevel= 1
UNET Pardiso=0
UNET DZMax Abort= 0
UNET Use Existing IB Tables= 0
UNET Froude Reduction=False
UNET Froude Limit= 0
UNET Froude Power= 0
UNET D1 Cores= 0
UNET WindReference=Eulerian
UNET WindDragFormulation=Hsu (1988)
UNET D2 Coriolis=0
UNET D2 Cores= 0
UNET D2 Theta= 1
UNET D2 Theta Warmup= 1
UNET D2 Z Tol= 0.01
UNET D2 Volume Tol= 0.01
UNET D2 Max Iterations= 20
UNET D2 Equation= 0
UNET D2 RampUpFraction=0.1
UNET D2 TimeSlices= 1
UNET D2 Turbulence Formulation=Non-Conservative (original)
UNET D2 Eddy Viscosity=0.3
UNET D2 Transverse Eddy Viscosity=0.1
UNET D2 Smagorinsky Mixing=0
UNET D2 BCVolumeCheck=0
UNET D2 Cores=0
UNET D2 SolverType=PARDISO (Direct)
UNET D2 Minimum Iterations= 2147483647
UNET D2 Maximum Iterations= 2147483647
UNET D2 Restart Number= 10
UNET D2 Relaxation Coeff=1.3
UNET D2 SOR Precondition Iterations= 10
UNET D2 ILUT Maximum Fill= 8
UNET D2 ILUT Tolerance=1E-08
UNET D1D2 MaxIter= 0
UNET D1D2 ZTol=0.01
UNET D1D2 QTol=0.1
UNET D1D2 MinQTol=1
Write IC File= 0
Write IC File at Fixed DateTime=0
Write IC File at Sim End=0
Echo Input=False
Echo Parameters=False
Echo Output=False
Write Detailed= 0
HDF Write Warmup=0
HDF Write Time Slices=0
HDF Flush=0
HDF Compression= 1
HDF Chunk Size= 1
HDF Spatial Parts= 1
HDF Use Max Rows=0
HDF Fixed Rows= 1
Calibration Method= 0
Calibration Iterations= 20
Calibration Max Change=0.05
Calibration Tolerance=0.2
Calibration Maximum=1.5
Calibration Minimum=0.5
Calibration Optimization Method= 1
WQ AD Non Conservative
WQ ULTIMATE=-1
WQ Max Comp Step=1HOUR
WQ Output Interval=15MIN
WQ Output Selected Increments= 0
WQ Output face flow=0
WQ Output face velocity=0
WQ Output face area=0
WQ Output face dispersion=0
WQ Output cell volume=0
WQ Output cell surface area=0
WQ Output cell continuity=0
WQ Output cumulative cell continuity=0
WQ Output face conc=0
WQ Output face dconc_dx=0
WQ Output face courant=0
WQ Output face peclet=0
WQ Output face adv mass=0
WQ Output face disp mass=0
WQ Output cell mass=0
WQ Output cell source sink temp=0
WQ Output nsm pathways=0
WQ Output nsm derived pathways=0
WQ Create Restart=0
WQ Fixed Restart=0
WQ System Summary=0
WQ Write To DSS=0
Sorting and Armoring Iterations= 10
XS Update Threshold= 0.02
Bed Roughness Predictor= 0
Hydraulics Update Threshold= 0.02
Energy Slope Method= 1
Volume Change Method= 1
Sediment Retention Method= 0
Sediment TS Multiplier= 1
Warm Up Method= 0
XS Weighting Method= 0
Number of US Weighted Cross Sections= 1
Number of DS Weighted Cross Sections= 1
Upstream XS Weight=0
Main XS Weight=1
Downstream XS Weight=0
Number of DS XS's Weighted with US Boundary= 1
Upstream Boundary Weight= 1
Weight of XSs Associated with US Boundary= 0
Number of US XS's Weighted with DS Boundary= 1
Downstream Boundary Weight= 0.5
Weight of XSs Associated with DS Boundary= 0.5
Percentile Method= 0
Sediment Output Level= 3
Mass or Volume Output= 0
Output Increment Type= 1
Profile and TS Output Increment= 1
Transport Output Increment 1
XS Output Flag= 0
XS Output Increment= 10
Read HDF5 Sediment Hotstart= 0
Sediment Hotstart Type= 0
Write Gradation File= 0
Read Gradation Hotstart= 0
Write HDF5 File= 1
Write Binary Output= 1
Write DSS Sediment File= 0
DSS Sediment Output Type= 1
SV Curve= 0
Specific Gage Flag= 0
Subcell Erosion Methods= 0
Subcell Deposition Methods= 0
Advection Scheme= 1
Matrix Solver= 0
Implicit Weighting Factor= 1
Maximum Outer Loop Convergence Iterations= 5
Convergence Maximum Absolute= 0.001
Convergence RMSE= 0.0001
Grain Fractions Max Abs Error= 0.001
Max Subgrid Regions= 1
Max Subgrid Length Scale= 3.402823E+38
Initial Layer Thickness= 3.402823E+38
Min Layer Thickness= 3.402823E+38
Max Layer Thickness= 3.402823E+38
Number of Layers= 5

--- SHOCKRN.f01 (steady flow) ---

Flow Title=Flow
Program Version=6.00
Number of Profiles= 6
Profile Names=01pct,10pct,04pct,02pct,0_2pct,01plus
River Rch & RM=SHOCKRN,Main            ,19622
     637     338     449     540     888     942
River Rch & RM=SHOCKRN,Main            ,15048
     944     508     670     802    1310    1400
River Rch & RM=SHOCKRN,Main            ,9046
    1460     801    1050    1250    2010    2160
River Rch & RM=SHOCKRN,Main            ,7997
    1630     895    1170    1390    2230    2410
River Rch & RM=SHOCKRN,Main            ,1129
    1930    1070    1390    1650    2640    2860
Boundary for River Rch & Prof#=SHOCKRN,Main            , 1
Up Type= 0
Dn Type= 3
Dn Slope=0.00968
Boundary for River Rch & Prof#=SHOCKRN,Main            , 2
Up Type= 0
Dn Type= 3
Dn Slope=0.00968
Boundary for River Rch & Prof#=SHOCKRN,Main            , 3
Up Type= 0
Dn Type= 3
Dn Slope=0.00968
Boundary for River Rch & Prof#=SHOCKRN,Main            , 4
Up Type= 0
Dn Type= 3
Dn Slope=0.00968
Boundary for River Rch & Prof#=SHOCKRN,Main            , 5
Up Type= 0
Dn Type= 3
Dn Slope=0.00968
Boundary for River Rch & Prof#=SHOCKRN,Main            , 6
Up Type= 0
Dn Type= 3
Dn Slope=0.00968
DSS Import GetInterval= 0
DSS Import GetPeak= 0
DSS Import FillOption= 0

--- SHOCKRN.g01 (geometry) ---

Geom Title=Geometry
Program Version=6.10

River Reach=SHOCKRN         ,Main
Reach XY= 30
2303634.85208751483498.990867087     2303255.663      483348.061
     2302659.747      482270.558     2301818.006       482126.65
     2300598.913      481553.802     2300007.504      481815.283
     2299703.372      482223.7972299371.97415906482376.387289141
2298929.37210105482463.6185116892298662.25814671482361.285808592
2298004.80304648482526.161719584     2297310.002      483210.616
2297048.91890181 483771.99951629 2296071.2402473484846.415106329
     2295583.267      485633.3842295758.63558787486040.587712944
2296120.86944824486185.372650621     2296262.708      486515.339
     2296656.134      486782.1642296776.19898565 487540.21193983
     2297417.864      487730.377     2297389.661      488163.633
     2297785.625      488742.397     2297595.688      489036.076
     2297631.267      489313.623     2297985.049      490067.196
2297613.21873257490124.755720212     2297568.824      490529.064
     2297243.459      490800.439     2296801.455      491671.595

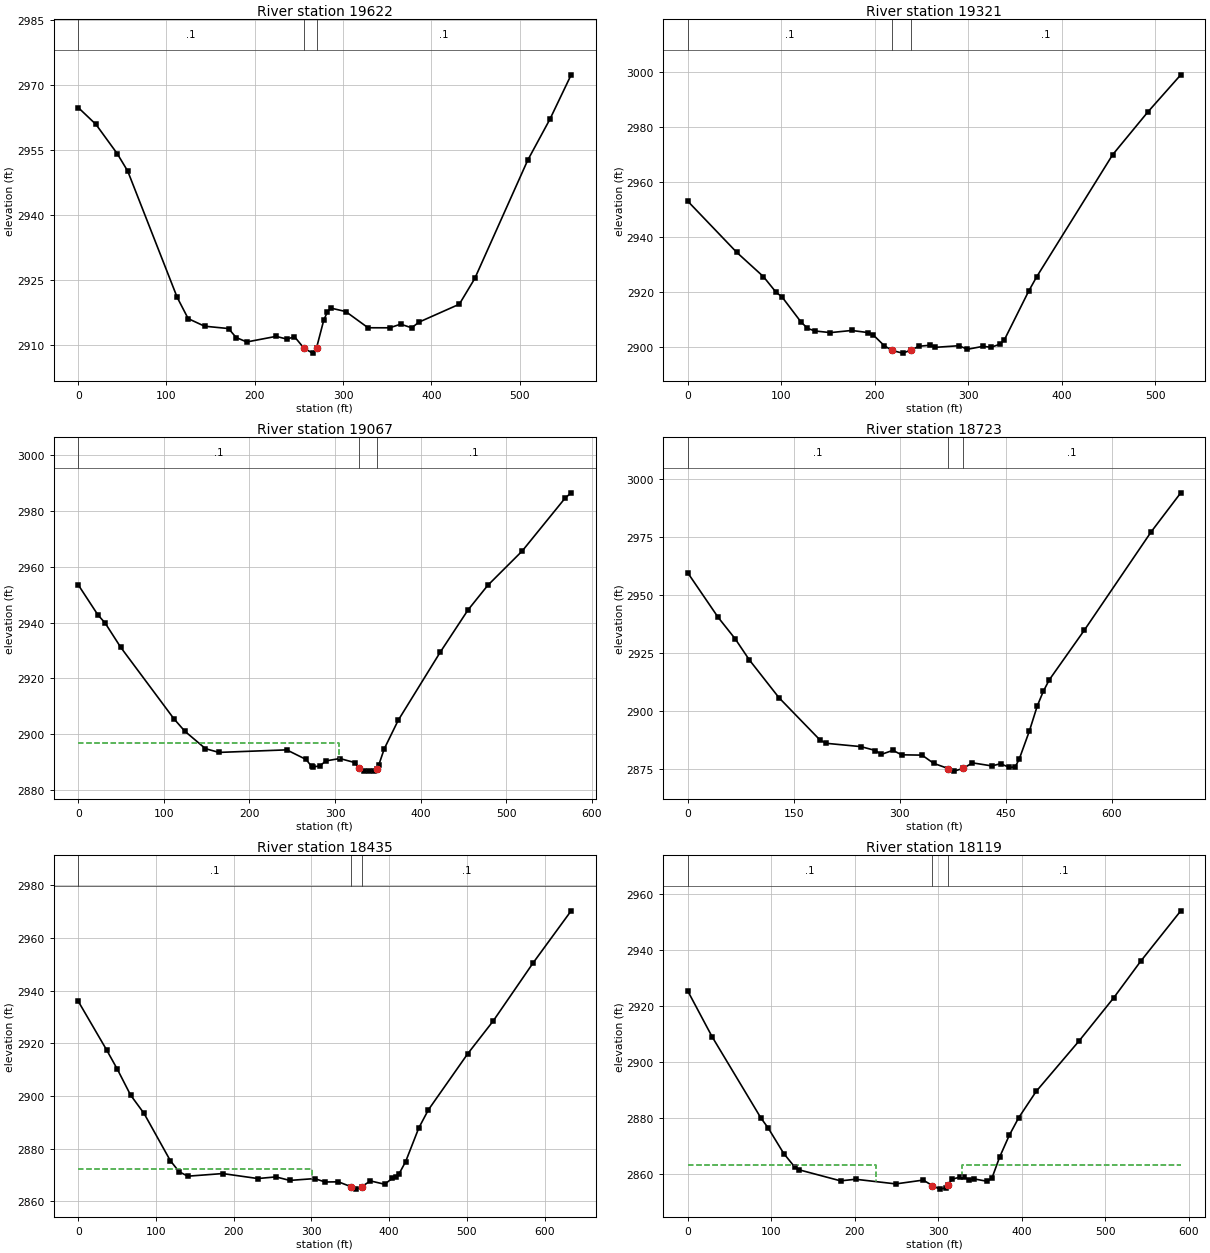
Type RM Length L Ch R = 1 ,19622   ,300.3,301,300.3
XS GIS Cut Line= 4
2303585.24228638483244.9611171052303582.70611921483360.081037959
2303672.27238285483682.3631843372303685.99075319483790.376960427
#Sta/Elev= 30
       0 2964.82    20.2  2960.9    44.3 2954.14    56.1 2950.14   112.2 2920.94
   124.6 2916.05   143.2  2914.3   170.3 2913.76     179 2911.68     191 2910.66
   224.2 2911.95   236.7 2911.31     245 2911.89     2562909.175   265.7 2908.08
     270 2909.26   278.2 2915.69   282.4 2917.63   286.5 2918.47   303.1 2917.69
   328.4 2913.94   352.9 2913.93   365.4 2914.77   377.8 2913.93   386.1 2915.24
   431.8 2919.38   449.3 2925.32   509.3 2952.65   534.4  2962.1   558.5 2972.37
#Mann= 3 ,-1,0
       0      .1       0     256    .045       0     270      .1       0
Bank Sta=256,270
XS Rating Curve= 0 ,0
Exp/Cntr=0.3,0.1

Type RM Length L Ch R = 1 ,19321   ,249.6,253.7,254
XS GIS Cut Line= 2
2303535.46660963483235.4018567652303225.31105528483661.748615769
#Sta/Elev= 30
       0 2953.09    52.3 2934.49    80.9 2925.63      94 2920.11     101 2918.14
     121 2909.15     128 2906.83   135.8 2905.86   152.5 2905.26   175.3 2906.04
   192.6 2905.28   198.3 2904.43   209.9 2900.55   218.4 2898.77   229.7 2897.79
   238.4 2898.83     247 2900.28   259.4 2900.67   264.4 2899.89     290 2900.49
     299 2899.19   315.7 2900.26   324.3 2899.93   333.6    2901   338.6 2902.66
   364.4 2920.26     373 2925.52   454.4 2970.05   491.9 2985.55   527.2 2999.11
#Mann= 3 ,-1,0
       0      .1       0   218.4    .045       0   238.4      .1       0
Bank Sta=218.4,238.4
XS Rating Curve= 0 ,0
Exp/Cntr(USF)=0,0
Exp/Cntr=0.3,0.1

Type RM Length L Ch R = 1 ,19067   ,332.6,343.8,350
XS GIS Cut Line= 3
2303485.92126845483087.7597215312303345.25036331483136.077117304
2303048.41185657483443.205180908
#Sta/Elev= 30
       0  2953.5      23 2942.73    31.5 2939.81    49.7 2931.13   111.8  2905.6
   124.5 2901.17   148.7 2894.91   164.4 2893.57   243.6 2894.48   266.3 2891.04
   272.7 2888.54   274.7 2888.34   282.7 2888.82   289.3 2890.54   305.7 2891.38
     323 2889.95   328.3 2887.85   333.8 2886.92   340.2 2886.88     346 2886.95
   348.92887.755   351.1 2889.02   357.5 2894.81   373.8 2905.02   422.9 2929.37
   455.3 2944.45   478.4 2953.26   518.7 2965.56   568.9 2984.49   575.9 2986.36
#Mann= 3 ,-1,0
       0      .1       0   328.3    .045       0   348.9      .1       0
#XS Ineff= 2 , 0
          304.23 2897.04
Permanent Ineff=
       F       F
Bank Sta=328.3,348.9
XS Rating Curve= 0 ,0
Exp/Cntr=0.3,0.1

Type RM Length L Ch R = 1 ,18723   ,299.3,288.9,282.3
XS GIS Cut Line= 4
2303451.13428367 482922.435224882303270.28829579482923.372250724
2302990.11756844482991.7751373332302826.13804575483150.132504964
#Sta/Elev= 30
       0 2959.55      43 2940.37      67 2931.17      87  2922.1     129  2905.8
   187.1 2887.57   195.4  2886.2   244.8 2884.76   265.4 2883.09   273.6  2881.4
   290.1 2883.16   302.4 2881.23   331.3  2881.1   347.7 2877.56   368.3 2875.33
   376.5 2874.21   389.3 2875.36   402.5 2877.77   430.1 2876.45   442.4 2877.41
   454.8 2875.79     463 2876.03   468.7 2879.35   483.1 2891.48   494.2 2902.22
   502.7 2908.51   511.2  2913.5   560.9 2934.92   655.5  2977.3   697.2 2994.02
#Mann= 3 ,-1,0
       0      .1       0   368.3    .045       0   389.3      .1       0
Bank Sta=368.3,389.3
XS Rating Curve= 0 ,0
Exp/Cntr(USF)=0,0
Exp/Cntr=0.3,0.1

Type RM Length L Ch R = 1 ,18435   ,313.4,315.4,311.5
XS GIS Cut Line= 2
2303139.60815298482517.0009490062302693.63947425482967.759559917
#Sta/Elev= 30
       0 2936.01    36.5 2917.53    50.4 2910.15    67.4 2900.35    84.7 2893.39
   118.6 2875.41   129.8 2871.27   140.9 2869.55   185.9 2870.55     231 2868.66
   254.3 2869.28   272.2 2867.95   304.1 2868.64   317.7 2867.35   334.7 2867.41
   350.5 2865.61   357.5 2864.64   364.6 2865.56   375.9 2867.76   394.1  2866.5
   404.2 2868.75   408.7 2869.16   412.7 2870.43   421.2 2875.09   438.1 2887.86
   450.4 2894.73     501 2916.03   533.8 2928.48   585.4 2950.64   634.1 2970.32
#Mann= 3 ,-1,0
       0      .1       0   350.5    .045       0   364.6      .1       0
#XS Ineff= 2 , 0
          300.73 2872.22
Permanent Ineff=
       F       F
Bank Sta=350.5,364.6
XS Rating Curve= 0 ,0
Exp/Cntr=0.3,0.1

Type RM Length L Ch R = 1 ,18119   ,232,232,234.4
XS GIS Cut Line= 3
2302985.38767006482318.4044064262302709.83327129482577.895482409
2302526.85943141482684.712296787
#Sta/Elev= 30
       0 2925.26    29.1 2908.94    87.7 2879.81    96.2 2876.33   114.9 2867.18
     128 2862.37   133.5 2861.33     183  2857.4   200.9 2857.97   249.1 2856.31
   281.9 2857.67   292.9 2855.72   301.6 2854.44   309.4 2854.89   311.3  2855.9
   316.9 2858.02   325.8 2858.72   331.1 2858.75   336.7 2857.77   342.5 2858.11
   358.8 2857.23   364.3 2858.41   373.5 2865.93     385 2873.68   396.2 2879.93
   417.2 2889.38   468.4 2907.36   510.1 2922.86   542.5 2935.97   590.4 2953.96
#Mann= 3 ,-1,0
       0      .1       0   292.9    .045       0   311.3      .1       0
#XS Ineff= 2 , 0
          225.78 2863.01  328.01         2863.05
Permanent Ineff=
       F       F
Bank Sta=292.9,311.3
XS Rating Curve= 0 ,0
Exp/Cntr=0.3,0.1

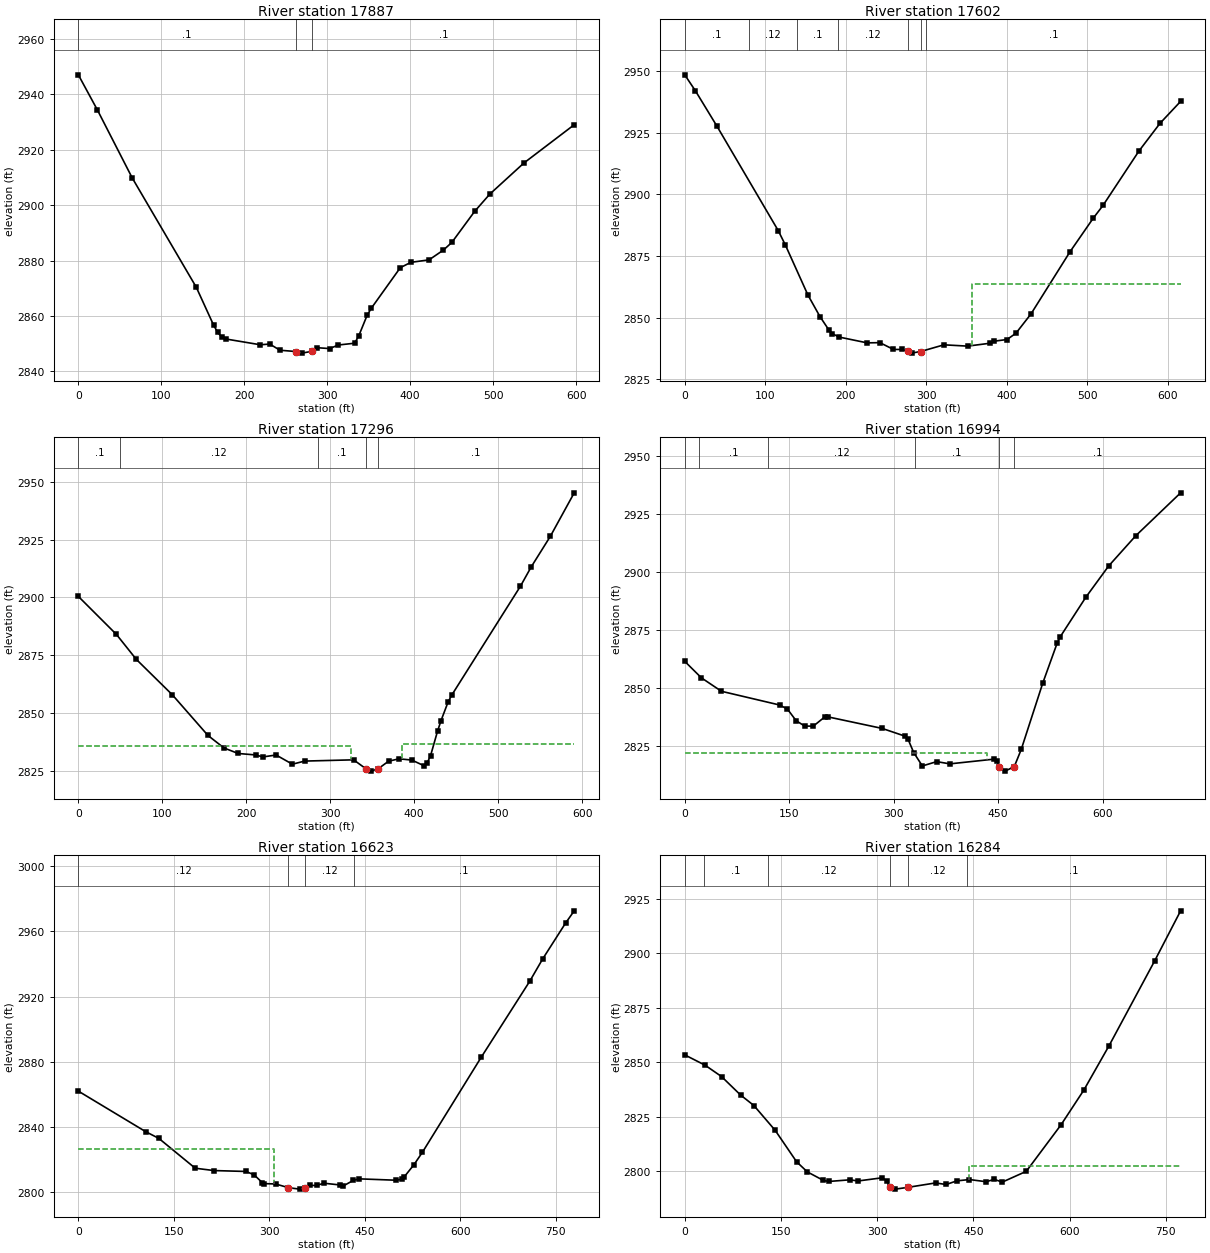
Type RM Length L Ch R = 1 ,17887   ,292.4,284.9,278.1
XS GIS Cut Line= 3
2302906.54652196482148.5077486822302576.85224353482396.067663014
2302486.62012522482558.022747156
#Sta/Elev= 30
       0    2947      23 2934.31      65 2909.77   142.2 2870.33     163  2856.7
     168 2854.03     173 2852.32     178 2851.67   219.3  2849.6   230.7 2849.85
   243.1 2847.62   262.2 2847.16   269.6 2846.58   282.2 2847.28   288.1 2848.53
   303.1 2848.22   313.1  2849.5   333.1 2850.16   338.1 2852.89   348.1 2860.24
   353.1 2862.77   388.1 2877.42   400.8 2879.34   422.7 2880.23   440.1 2883.78
   450.2 2886.53   477.7 2897.73   495.9 2903.94   537.1 2915.19   597.7 2928.99
#Mann= 3 ,-1,0
       0      .1       0   262.2    .045       0   282.2      .1       0
Bank Sta=262.2,282.2
XS Rating Curve= 0 ,0
Exp/Cntr(USF)=0,0
Exp/Cntr=0.3,0.1

Type RM Length L Ch R = 1 ,17602   ,305.6,306.4,300.9
XS GIS Cut Line= 2
2302569.91131135481933.3388511782302293.43084628482483.986137262
#Sta/Elev= 30
       0 2948.51    13.2 2942.06    39.9 2927.75   116.2 2885.32   125.1 2879.46
   153.1 2859.19     168 2850.49   178.9 2845.14   183.3 2843.55   191.9 2842.16
   226.7 2839.81   242.5  2839.9   259.4 2837.14   269.4 2837.14   277.3 2836.33
   281.8 2835.65   293.2 2836.31   322.1 2839.02   351.5 2838.49   379.6 2839.67
   384.7  2840.5   400.5 2841.17   411.6 2843.73   430.3 2851.56   478.7 2876.73
   507.7 2890.41   519.7 2895.52   564.3 2917.56   590.6 2928.85   616.2 2937.74
#Mann= 7 ,-1,0
       0      .1       0      80     .12       0     140      .1       0
     190     .12       0   277.3    .045       0   293.2     .12       0
     300      .1       0
#XS Ineff= 2 , 0
                          356.98         2863.71
Permanent Ineff=
       F       F
Bank Sta=277.3,293.2
XS Rating Curve= 0 ,0
Exp/Cntr(USF)=0,0
Exp/Cntr=0.3,0.1

Type RM Length L Ch R = 1 ,17296   ,302.4,302.1,302.7
XS GIS Cut Line= 3
2302317.68257624481865.691601225 2302208.0584666482002.994966852
 2302093.2754411482401.551577254
#Sta/Elev= 30
       0 2900.39    45.4 2883.91      69 2873.15     112 2857.77   154.4 2840.18
   173.4 2834.79   190.3 2832.39   211.3 2831.75   219.6 2830.89   235.5 2831.73
   254.9 2827.75   269.5  2829.1   327.8 2829.64   342.2 2825.84   348.6 2824.75
     357 2825.75   369.4 2829.04   381.9 2830.08   397.1 2829.54   411.1 2827.17
   415.2 2828.16   419.4  2831.4   427.7 2842.01   431.9 2846.62   440.2 2854.58
   444.4 2857.51   526.4 2904.77   539.3 2913.17     562 2926.36   590.5 2945.23
#Mann= 5 ,-1,0
       0      .1       0      50     .12       0   285.7      .1       0
   342.2    .045       0     357      .1       0
#XS Ineff= 2 , 0
          324.51 2835.48  385.01         2836.36
Permanent Ineff=
       F       F
Bank Sta=342.2,357
XS Rating Curve= 0 ,0
Exp/Cntr=0.3,0.1

Type RM Length L Ch R = 1 ,16994   ,371.8,371,372.9
XS GIS Cut Line= 2
2301973.97007649481689.9957797042301803.10423712 482381.26043294
#Sta/Elev= 30
       0 2861.59    23.9 2854.49    52.7 2848.69   136.3 2842.78   147.5 2841.02
   159.9 2836.05   172.2 2833.71   184.6 2833.68   201.1 2837.65   205.2  2837.7
   283.5  2832.7   316.4 2829.36   320.5 2828.16   328.8 2822.31   341.2 2816.54
   361.8  2818.4   380.7 2817.44   444.2 2819.47   448.3 2818.74  451.63  2816.3
     460 2814.31   473.2 2816.23   483.2 2823.63   514.2 2852.28   534.8 2869.43
   538.9 2872.01     576  2889.2     609 2902.74   647.7 2915.67   712.1 2934.15
#Mann= 6 ,-1,0
       0     .12       0      20      .1       0     120     .12       0
     330      .1       0  451.63    .045       0   473.2      .1       0
#XS Ineff= 2 , 0
          433.71 2822.27
Permanent Ineff=
       F       F
Bank Sta=451.63,473.2
XS Rating Curve= 0 ,0
Exp/Cntr=0.3,0.1

Type RM Length L Ch R = 1 ,16623   ,336.4,338.7,336.5
XS GIS Cut Line= 4
2301739.55046558481616.1102621132301636.35593347481755.188258622
2301527.61466269482086.039359084 2301504.0159485482342.804135645
#Sta/Elev= 30
       0 2862.01   105.9 2837.12   126.5 2833.01   183.7  2814.7   213.2 2813.26
   263.6 2812.71   276.3 2810.62     289 2805.88   292.2 2805.25     310 2805.04
   330.2 2802.75   347.9 2801.87   356.3 2802.66   364.7 2804.14   374.5 2804.13
   385.8  2805.5   411.1 2804.44   415.7 2803.68   432.1 2807.22   441.1 2808.18
   499.5 2807.33   507.9 2807.95   512.1 2809.37   527.5 2816.89   540.7 2824.47
   633.1 2882.76   709.4 2929.43   729.8 2943.17   765.6 2965.05   779.3 2972.64
#Mann= 4 ,-1,0
       0     .12       0   330.2    .045       0   356.3     .12       0
  433.18      .1       0
#XS Ineff= 2 , 0
          306.98 2826.78
Permanent Ineff=
       F       F
Bank Sta=330.2,356.3
XS Rating Curve= 0 ,0
Exp/Cntr=0.3,0.1

Type RM Length L Ch R = 1 ,16284   ,339.5,338.2,336
XS GIS Cut Line= 2
2301395.73695132481485.6487257282301180.56805381482228.328468723
#Sta/Elev= 30
       0 2853.41    31.6 2848.69    57.4 2843.44      87 2834.98   107.8 2830.14
   141.1  2818.7   174.4  2804.3   191.1 2799.65   216.1 2795.74   224.4 2795.24
   257.6    2796   270.2 2795.47   307.7 2796.92   314.7 2795.56   320.2 2792.57
   328.5 2791.72     348 2792.54     391 2794.56   407.6 2793.85   424.3 2795.52
     444 2796.12   470.1 2795.12   482.6 2796.21   495.1 2794.94   532.6 2799.91
   586.7 2821.26   622.5 2837.33   661.7 2857.67   732.5 2896.48   773.2  2919.6
#Mann= 6 ,-1,0
       0     .12       0      30      .1       0     130     .12       0
   320.2    .045       0     348     .12       0     440      .1       0
#XS Ineff= 2 , 0
                          442.59         2802.51
Permanent Ineff=
       F       F
Bank Sta=320.2,348
XS Rating Curve= 0 ,0
Exp/Cntr(USF)=0,0
Exp/Cntr=0.3,0.1

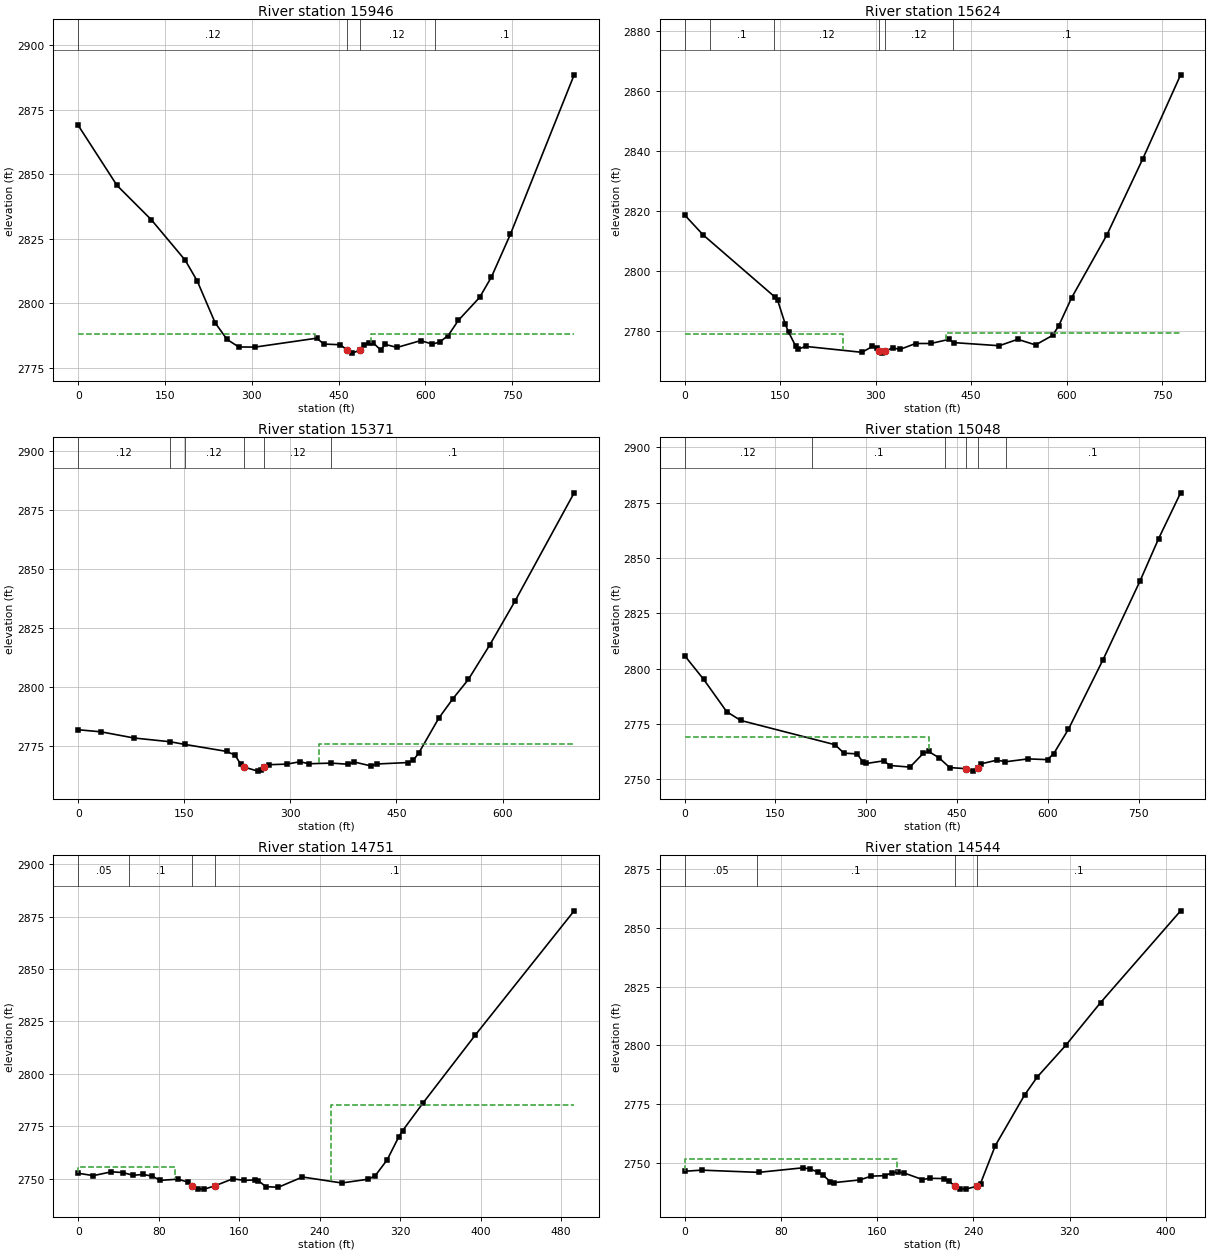
Type RM Length L Ch R = 1 ,15946   ,318.5,321.7,322.4
XS GIS Cut Line= 3
     2301154.825      481343.8212301018.61296967 481536.54889503
2300895.58186436482145.138390106
#Sta/Elev= 30
       0 2868.97      67  2845.7   126.3  2832.4   184.8 2816.73   205.6 2808.69
   236.6 2792.45   257.1 2786.01   277.5 2783.08     306 2783.05   412.1 2786.49
   424.4 2784.22   452.9 2783.95   465.2 2781.79   473.3  2780.7   486.52781.803
   493.7 2783.94   501.9 2784.53   510.1 2784.62   522.3 2781.96   530.9 2784.06
   550.9 2782.91   591.5 2785.53   612.1 2784.21   624.3 2784.96   639.2 2787.52
     657 2793.44   693.5 2802.28   713.9 2810.17   746.8  2826.8   856.9 2888.56
#Mann= 4 ,-1,0
       0     .12       0   465.2    .045       0   486.5     .12       0
     616      .1       0
#XS Ineff= 2 , 0
          408.68 2788.09   506.6         2787.93
Permanent Ineff=
       F       F
Bank Sta=465.2,486.5
XS Rating Curve= 0 ,0
Exp/Cntr=0.3,0.1

Type RM Length L Ch R = 1 ,15624   ,250.7,252.9,251.4
XS GIS Cut Line= 3
 2300867.0692838481381.5347430652300735.19157242481432.434912367
2300687.97191484482068.445940846
#Sta/Elev= 30
       0 2818.56    28.8 2811.95   142.1 2791.12   146.1 2790.04   158.1 2782.08
   163.5 2779.37   174.2 2774.86   178.2 2773.82   190.2  2774.7   278.5 2772.73
   294.9 2774.69   301.7 2774.24   305.4 2773.31   310.6 2772.46   314.6 2773.16
   326.6 2774.17   338.6 2773.73   362.7 2775.67   386.8 2775.68   414.9 2777.04
   422.9 2775.97   494.2 2774.93   523.2 2777.07   551.2  2775.2     578 2778.39
   587.3 2781.45   607.9 2790.95   663.2 2811.88   719.9 2837.41   779.1 2865.34
#Mann= 6 ,-1,0
       0     .12       0      40      .1       0     140     .12       0
   305.4    .045       0   314.6     .12       0  421.36      .1       0
#XS Ineff= 2 , 0
          248.23 2778.95  410.33         2779.02
Permanent Ineff=
       F       F
Bank Sta=305.4,314.6
XS Rating Curve= 0 ,0
Exp/Cntr=0.3,0.1

Type RM Length L Ch R = 1 ,15371   ,331.8,323,316
XS GIS Cut Line= 3
2300605.02767146481385.3051259762300509.93596811481545.919926316
2300504.98398854482060.589274433
#Sta/Elev= 30
       0 2781.86    32.4 2780.97    78.9 2778.36     130 2776.77   150.9 2775.63
   209.9 2772.67   221.9 2771.06   229.9 2767.12   233.9 2766.09   253.9  2764.3
   257.9 2764.67   262.82766.033   269.9 2767.03   294.6 2767.27   313.9 2768.29
   325.9 2767.43   357.8  2767.7   381.9 2767.22   389.9  2768.2   413.9 2766.51
   421.9 2767.32   465.9 2767.94   473.9 2768.92   481.9 2772.17   509.9 2786.79
   529.9 2795.05   551.7  2803.2   581.9 2817.81   617.9 2836.58   701.3 2882.41
#Mann= 6 ,-1,0
       0     .12       0     130      .1       0   150.9     .12       0
   233.9    .045       0   262.8     .12       0   357.8      .1       0
#XS Ineff= 2 , 0
                             340         2776.01
Permanent Ineff=
       F       F
Bank Sta=233.9,262.8
XS Rating Curve= 0 ,0
Exp/Cntr(USF)=0,0
Exp/Cntr=0.3,0.1

Type RM Length L Ch R = 1 ,15048   ,304.9,297.2,288.2
XS GIS Cut Line= 2
     2300045.426      481320.4442300375.15124579482070.449975012
#Sta/Elev= 30
       0 2805.86    31.4 2795.13    69.4 2780.54    92.6 2776.58   248.5  2765.6
     263  2761.8   284.9 2761.46     294 2757.95   300.1 2757.12   328.5 2758.31
   339.5 2756.21   372.2 2755.49   394.2 2761.72   402.8  2762.6   420.3 2759.67
   437.8 2755.27     464 2754.81   477.1 2753.67   485.2 2755.02   490.2 2756.99
   516.4 2758.68   529.5 2757.88   567.2  2759.2   599.4 2758.87   609.7  2761.6
     634 2772.62   691.2 2804.08   752.3 2839.66   782.9 2858.74   819.3 2879.47
#Mann= 6 ,-1,0
       0     .12       0     210      .1       0     430     .12       0
     464    .045       0   485.2     .12       0     530      .1       0
#XS Ineff= 2 , 0
          403.94  2769.2
Permanent Ineff=
       F       F
Bank Sta=464,485.2
XS Rating Curve= 0 ,0
Exp/Cntr=0.3,0.1

Type RM Length L Ch R = 1 ,14751   ,205.1,207.1,210.2
XS GIS Cut Line= 3
2299876.03007749481775.2228963142300125.90363588481957.422365974
2300225.85305924482111.511060315
#Sta/Elev= 30
       0 2752.61      15 2751.48      33  2753.3    44.1 2752.96    54.6 2751.65
    64.5 2752.03    73.1 2751.29    81.7 2749.23    99.2 2749.78   109.1 2748.38
   113.12746.643     119 2745.09   125.5 2745.04     1362746.645   153.6 2749.96
   164.7 2749.22   176.1 2749.42     179 2749.05   186.6 2746.19     199 2745.96
   222.9 2750.82     262 2747.97   288.5 2749.79   295.3  2751.5   307.1 2759.05
   318.5 2769.89   322.3 2772.86   342.5    2786   394.8 2818.62   492.9 2877.78
#Mann= 4 ,-1,0
       0     .05       0      50      .1       0   113.1    .045       0
     136      .1       0
#XS Ineff= 2 , 0
           96.34 2755.83  251.66         2785.07
Permanent Ineff=
       F       F
Bank Sta=113.1,136
XS Rating Curve= 0 ,0
Exp/Cntr(USF)=0,0
Exp/Cntr=0.3,0.1

Type RM Length L Ch R = 1 ,14544   ,272.7,272.2,270.1
XS GIS Cut Line= 2
2299752.13443812481858.5140824442300020.40911382482171.751262316
#Sta/Elev= 30
       0 2746.44      14 2746.91    61.5 2745.97    98.4 2747.91   104.6 2747.37
   110.7 2746.07   115.4 2744.66   121.1    2742   123.9 2741.59   145.7 2742.76
   155.1 2744.36   166.8 2744.58     172 2745.77   177.3 2746.07   182.6 2745.68
   197.7 2742.91   203.6 2743.44   215.3 2743.33   219.4 2742.42   224.7 2740.08
   228.9 2739.06   233.7 2738.84   243.1 2740.08     246 2741.22   258.3 2757.33
   282.6 2778.82   293.2 2786.54   316.8 2799.95   345.8 2818.14   412.4 2857.19
#Mann= 4 ,-1,0
       0     .05       0      60      .1       0   224.7    .045       0
   243.1      .1       0
#XS Ineff= 2 , 0
           176.9 2751.83
Permanent Ineff=
       F       F
Bank Sta=224.7,243.1
XS Rating Curve= 0 ,0
Exp/Cntr=0.3,0.1

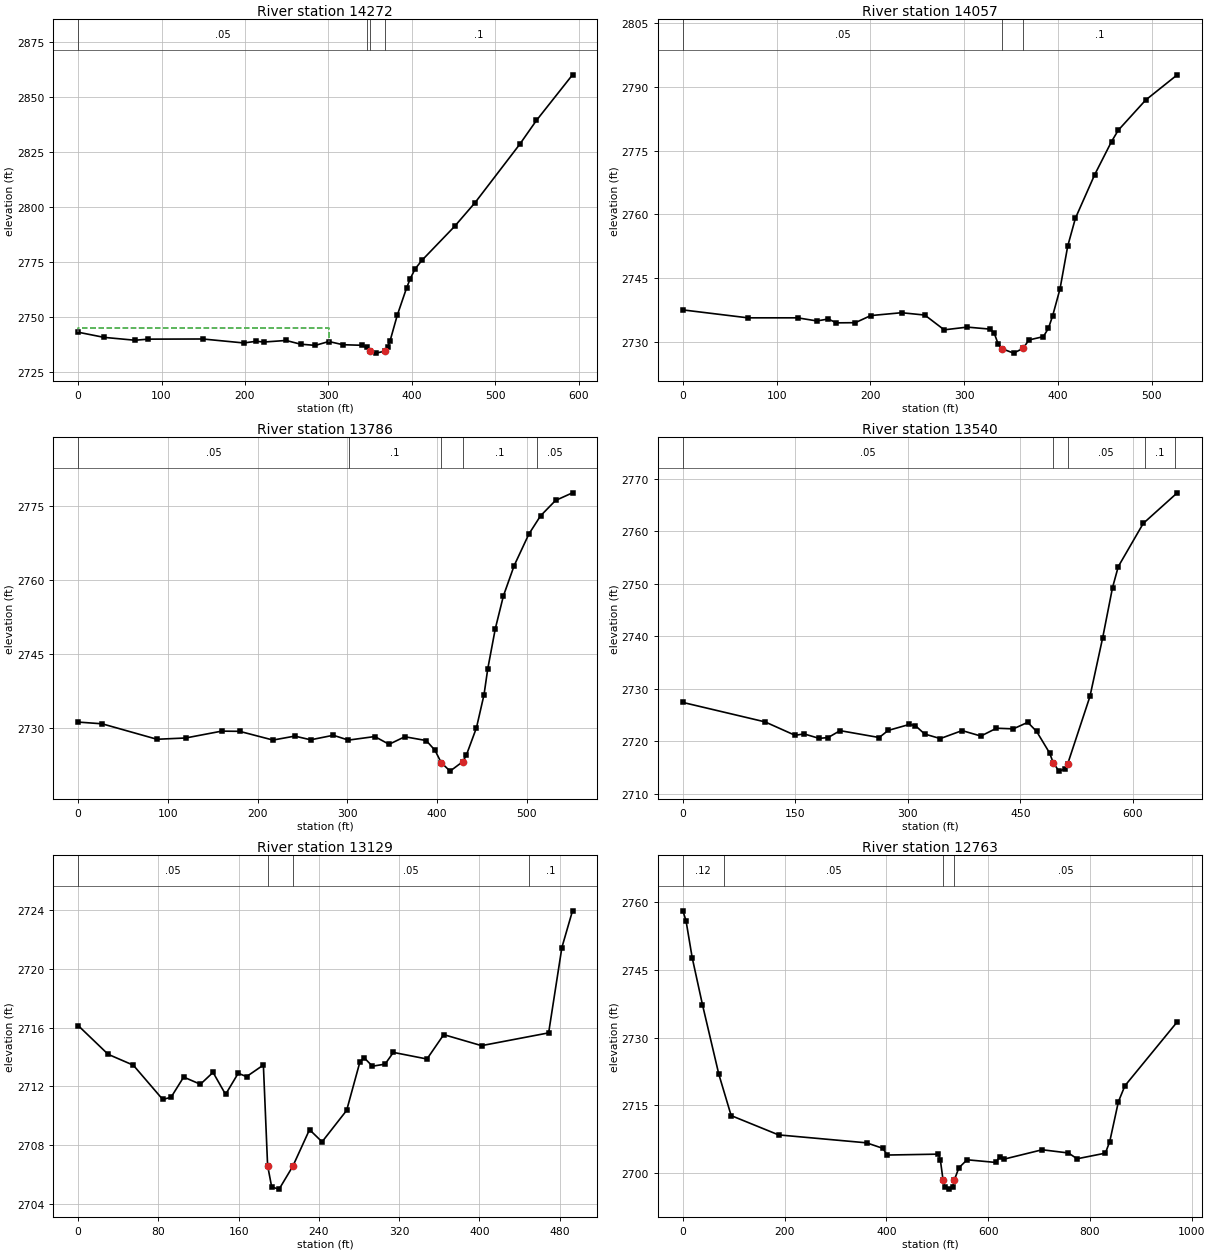
Type RM Length L Ch R = 1 ,14272   ,207,214.8,222.9
XS GIS Cut Line= 3
2299573.85271791481898.8463360442299619.98278156482120.641967146
2299880.91041712482377.713529277
#Sta/Elev= 30
       0 2743.21      31 2740.87    68.2 2739.56    84.1 2740.06   149.5 2740.13
   198.5 2738.33   213.6 2739.08     223 2738.75   249.3 2739.46   266.7 2737.77
   284.3 2737.22   300.6 2738.98   317.6 2737.52   340.2 2737.27   345.9 2736.28
   350.32734.776   357.2  2733.7   368.5 2734.66   371.3 2736.56   374.1 2739.35
   382.6 2750.84   393.9 2763.41   398.3 2767.58     404 2771.96   412.1 2775.84
   451.4 2791.33     476 2802.15   529.4  2828.6   549.5 2839.49   592.8 2860.25
#Mann= 4 ,-1,0
       0     .05       0  346.54      .1       0   350.3    .045       0
   368.5      .1       0
#XS Ineff= 2 , 0
          300.47 2745.28
Permanent Ineff=
       F       F
Bank Sta=350.3,368.5
XS Rating Curve= 0 ,0
Exp/Cntr(USF)=0,0
Exp/Cntr=0.3,0.1

Type RM Length L Ch R = 1 ,14057   ,272.4,271.4,270.6
XS GIS Cut Line= 3
2299435.94810854481950.0935490022299488.40963005 482173.92309478
2299559.57096446 482462.54714478
#Sta/Elev= 30
       0 2737.59    69.3 2735.73   122.3 2735.73   142.9    2735   155.2 2735.46
   163.4 2734.55   183.9 2734.59   200.4 2736.26   233.2 2736.93     258 2736.38
   278.7 2732.91   303.3 2733.55     328 2733.07   332.1 2732.09   336.2 2729.58
   340.4 2728.47   352.7 2727.44   362.6 2728.54   369.2 2730.54   384.4 2731.31
   389.8 2733.26   394.3 2736.18   402.2 2742.55   410.4 2752.57   418.6 2759.12
   439.2 2769.37   457.1 2777.12   464.3 2779.79   493.5 2786.87   527.2  2792.8
#Mann= 3 ,-1,0
       0     .05       0   340.4    .045       0   362.6      .1       0
Bank Sta=340.4,362.6
XS Rating Curve= 0 ,0
Exp/Cntr=0.3,0.1

Type RM Length L Ch R = 1 ,13786   ,244.4,245.1,245.9
XS GIS Cut Line= 3
2299216.62786186 482001.542330622299206.01187796482192.883357683
2299314.88632561482535.108639574
#Sta/Elev= 30
       0 2731.22    26.7 2730.87    87.8 2727.73   119.8 2727.99   159.9 2729.38
   179.9 2729.34   217.1 2727.57   241.4 2728.37   259.1 2727.62   284.3 2728.54
   301.1 2727.56   330.5 2728.28   346.4 2726.71     364 2728.24   387.8 2727.47
   397.6 2725.49   404.5 2722.99   414.4 2721.26   428.52723.177   432.4 2724.44
   443.8 2730.07   452.2 2736.77   456.4 2742.06   464.8 2750.19   473.8 2756.83
   485.8 2762.99   502.2  2769.4   515.2  2773.1   531.9 2776.22   550.8 2777.77
#Mann= 5 ,-1,0
       0     .05       0  301.64      .1       0   404.5    .045       0
   428.5      .1       0  511.64     .05       0
Bank Sta=404.5,428.5
XS Rating Curve= 0 ,0
Exp/Cntr(USF)=0,0
Exp/Cntr=0.3,0.1

Type RM Length L Ch R = 1 ,13540   ,413,411,409.1
XS GIS Cut Line= 3
2298964.50529416481955.7742372012298978.93199808482261.435774251
2299076.72300935482600.733841064
#Sta/Elev= 30
       0 2727.43   109.5 2723.73   149.6 2721.17   161.5 2721.44   181.6 2720.59
   193.6 2720.74   209.6 2722.06   261.7 2720.75   273.7  2722.1   301.7 2723.23
   309.9 2723.02   322.4 2721.41   343.2 2720.55   372.3 2722.07   397.3 2721.03
   418.1 2722.52   440.5  2722.4   459.8 2723.64   471.6 2721.91   488.9 2717.81
   493.72715.965   501.4 2714.35   509.7 2714.78   512.92715.668   542.7 2728.57
   559.7 2739.76   572.8  2749.3   580.5 2753.31   613.8 2761.53   659.1 2767.35
#Mann= 5 ,-1,0
       0     .05       0   493.7    .045       0   512.9     .05       0
     616      .1       0     656     .05       0
Bank Sta=493.7,512.9
XS Rating Curve= 0 ,0
Exp/Cntr=0.3,0.1

Type RM Length L Ch R = 1 ,13129   ,362.9,366.7,368.8
XS GIS Cut Line= 2
2298590.46830419482168.6043768152298734.71401405482639.902240724
#Sta/Elev= 30
       0 2716.15    29.9 2714.19      55 2713.45    84.3 2711.12    92.6 2711.26
   105.2 2712.64   121.9 2712.15   134.5 2712.96     147 2711.46   159.6  2712.9
   167.9 2712.67   184.7 2713.46   188.92706.618     193 2705.15   200.4 2705.01
     2142706.563   230.7 2709.06   243.2 2708.23   267.7 2710.37   280.9 2713.66
   285.1 2713.96   293.4 2713.38     306 2713.52   314.3 2714.32   347.8 2713.87
   364.5 2715.53   402.2 2714.78   469.1 2715.65   482.3 2721.46   492.9 2723.96
#Mann= 4 ,-1,0
       0     .05       0   188.9    .045       0     214     .05       0
     450      .1       0
Bank Sta=188.9,214
XS Rating Curve= 0 ,0
Exp/Cntr(USF)=0,0
Exp/Cntr=0.3,0.1

Type RM Length L Ch R = 1 ,12763   ,281.1,276.2,271.7
XS GIS Cut Line= 3
2298244.18326933481930.9904685662298326.44616922482581.381520757
 2298437.0643284482877.576284379
#Sta/Elev= 30
       0 2758.13     6.2 2755.92    18.3 2747.75    38.5 2737.31    70.7 2721.86
    94.9 2712.71   188.1 2708.43     361 2706.67   393.3 2705.44   401.4 2703.96
   502.2 2704.16   506.2 2702.77   511.42698.397   514.3 2696.94   522.3  2696.4
   530.4 2696.87   533.3 2698.36   542.5 2701.13   558.6 2702.91     615 2702.32
   623.1 2703.62   631.2 2703.05   706.2 2705.13   757.8 2704.42   774.8 2703.13
   830.4 2704.38     839 2706.94     856 2715.78   868.8 2719.32   971.7  2733.5
#Mann= 4 ,-1,0
       0     .12       0      80     .05       0   511.4    .045       0
   533.3     .05       0
Bank Sta=511.4,533.3
XS Rating Curve= 0 ,0
Exp/Cntr=0.3,0.1

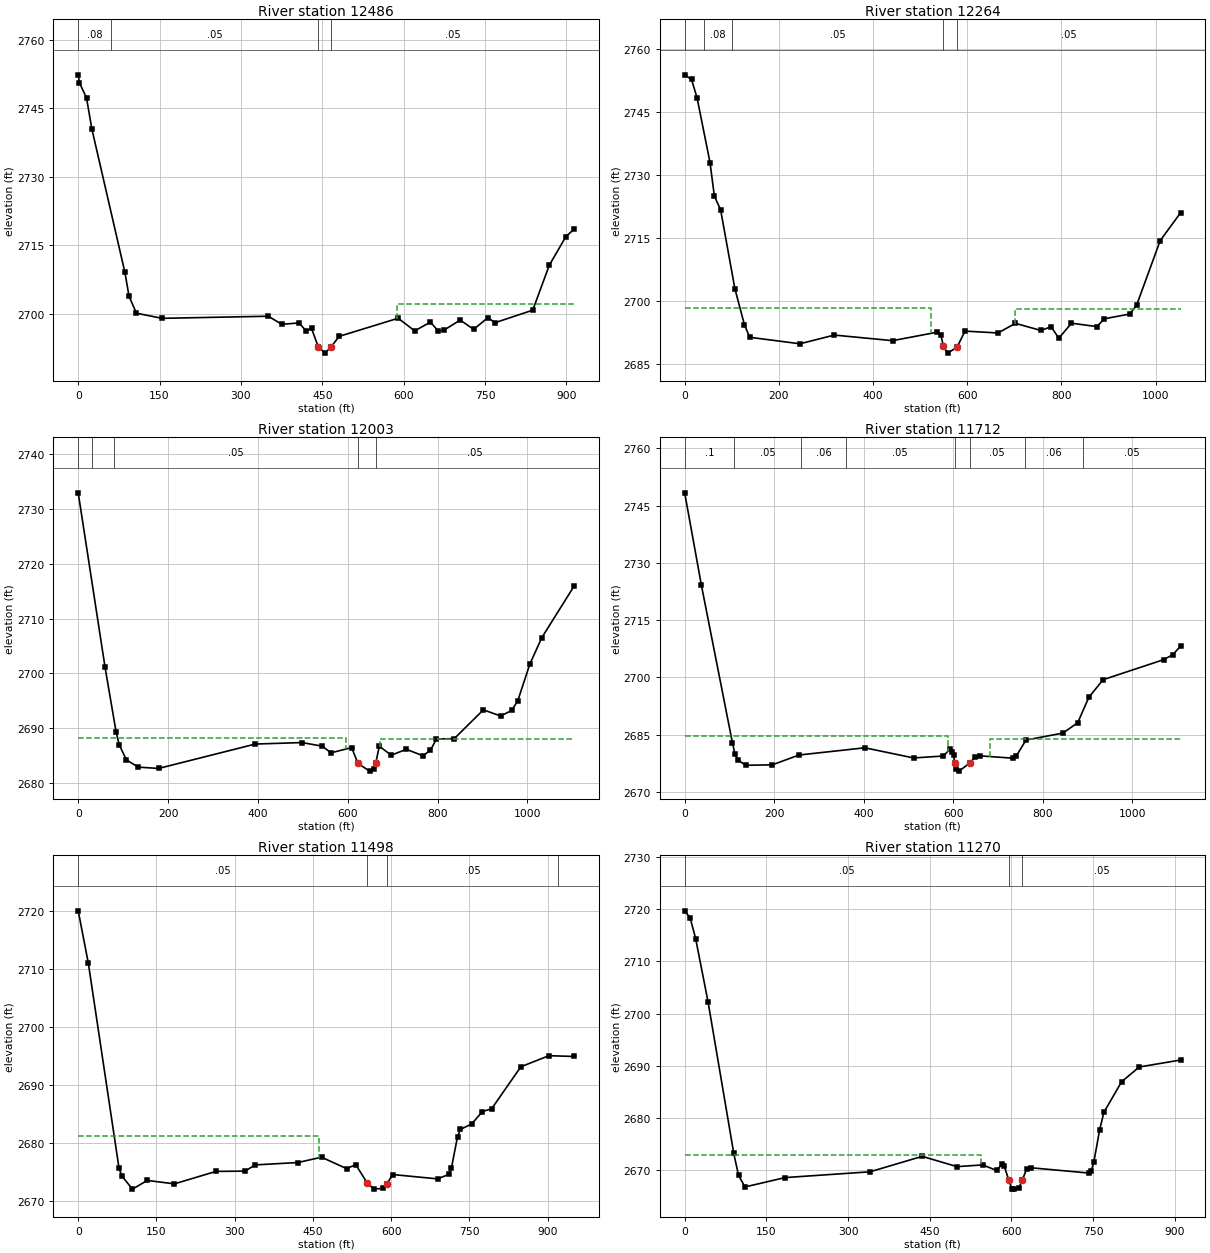
Type RM Length L Ch R = 1 ,12486   ,227.9,222.2,216
XS GIS Cut Line= 2
     2297861.323      482091.048     2298221.933      482931.306
#Sta/Elev= 30
       0 2752.29     2.3 2750.57    15.4 2747.18    25.1 2740.47      86 2709.08
    93.7 2703.82   107.3 2700.09   154.7 2698.97   350.5 2699.43   375.4 2697.66
   407.1 2697.96   420.2 2696.24   430.2 2696.75   442.4  2692.8     455 2691.35
   466.7 2692.78   481.1 2695.02   589.9 2698.99   620.4 2696.23   649.5 2698.14
   663.9 2696.17   673.8 2696.34   704.3 2698.58   729.2 2696.56   755.4 2699.13
   768.4 2698.01   838.1 2700.76   868.5 2710.58   899.2 2716.87   914.4 2718.51
#Mann= 4 ,-1,0
       0     .08       0      60     .05       0   442.4    .045       0
   466.7     .05       0
#XS Ineff= 2 , 0
                          588.17         2702.05
Permanent Ineff=
       F       F
Bank Sta=442.4,466.7
XS Rating Curve= 0 ,0
Exp/Cntr=0.3,0.1

Type RM Length L Ch R = 1 ,12264   ,265.1,261.2,257.1
XS GIS Cut Line= 3
2297461.37215177 482226.832583372297826.47420442482597.460539114
2298182.74351862482993.477108657
#Sta/Elev= 30
       0 2753.77    14.5 2752.68    26.3  2748.3    53.8 2732.94      63 2724.99
    76.3  2721.7   106.6 2702.97   126.8 2694.45     138 2691.44   244.7  2689.9
   317.7 2691.97   441.3 2690.64     536 2692.65   543.9 2692.03   549.32689.278
   558.1 2687.68     5782689.053   595.2 2692.91   665.1 2692.47   702.2 2694.75
     756 2693.07   778.1 2693.94   794.3 2691.21   821.2 2694.79     875 2693.98
   891.1 2695.84   944.9 2696.97   959.4 2699.05  1009.5 2714.39  1052.9 2721.03
#Mann= 5 ,-1,0
       0     .05       0      40     .08       0     100     .05       0
   549.3    .045       0     578     .05       0
#XS Ineff= 2 , 0
          523.94 2698.49  701.07         2698.09
Permanent Ineff=
       F       F
Bank Sta=549.3,578
XS Rating Curve= 0 ,0
Exp/Cntr(USF)=0,0
Exp/Cntr=0.3,0.1

Type RM Length L Ch R = 1 ,12003   ,286.5,291,291.9
XS GIS Cut Line= 2
 2297176.6323471482449.067512663     2298062.355      483108.136
#Sta/Elev= 30
       0 2732.99    59.8 2701.08    84.2 2689.34    91.2 2686.95   107.4 2684.16
     134 2682.85   178.9 2682.61   394.3 2687.07     498 2687.34   542.9 2686.69
   562.9 2685.47   608.7 2686.42   622.7 2683.53   648.7 2682.12   657.6 2682.43
   662.6 2683.69   670.2 2686.66     697 2685.04   730.5 2686.11   767.3 2684.93
   784.1 2685.93   797.5    2688   837.1 2688.06   901.9 2693.32   940.3  2692.2
   965.1 2693.21   978.5 2694.98  1005.3 2701.67  1031.7 2706.48    1104 2715.96
#Mann= 5 ,-1,0
       0     .05       0      30      .1       0      80     .05       0
   622.7    .045       0   662.6     .05       0
#XS Ineff= 2 , 0
          595.98  2688.1     672         2688.08
Permanent Ineff=
       F       F
Bank Sta=622.7,662.6
XS Rating Curve= 0 ,0
Exp/Cntr=0.3,0.1

Type RM Length L Ch R = 1 ,11712   ,214.2,214.4,214.4
XS GIS Cut Line= 2
2297026.92121177482617.5813578092297848.26485278483361.803530178
#Sta/Elev= 30
       0 2748.34    37.4 2724.12   106.6 2682.96   112.6 2679.88   118.5 2678.42
   136.4    2677     196 2677.12   255.5 2679.69   402.7 2681.58   511.7 2678.92
   578.3 2679.43   592.5 2681.22   598.1 2680.57     601 2679.57   603.8 2677.51
   606.6 2675.98     613 2675.47   636.8 2677.54   649.4 2679.17   660.4 2679.47
   734.1 2678.85   741.2 2679.43   762.8 2683.61   845.3 2685.43   878.5 2688.15
   903.1 2694.76   935.1 2699.41  1070.5 2704.66  1090.9 2705.97  1108.4 2708.21
#Mann= 8 ,-1,0
       0      .1       0     110     .05       0     260     .06       0
     360     .05       0   603.8    .045       0   636.8     .05       0
     760     .06       0     890     .05       0
#XS Ineff= 2 , 0
          587.49 2684.57  681.46         2683.87
Permanent Ineff=
       F       F
Bank Sta=603.8,636.8
XS Rating Curve= 0 ,0
Exp/Cntr(USF)=0,0
Exp/Cntr=0.3,0.1

Type RM Length L Ch R = 1 ,11498   ,232.7,227.8,222.2
XS GIS Cut Line= 2
2296914.31202669 482796.006173552297612.27825633483441.453614142
#Sta/Elev= 30
       0 2720.09    19.4 2711.05    78.3 2675.63    84.2 2674.25     104 2672.05
   132.4 2673.55   184.4 2672.96   264.1 2675.11   319.9 2675.16     339 2676.23
   421.1 2676.64   466.4 2677.56   514.5 2675.59     532 2676.28   554.1 2673.09
   567.3 2672.07     585 2672.18   591.7 2672.93   602.7 2674.57     689 2673.82
   710.8 2674.61   715.5 2675.74   727.1 2681.09   732.6 2682.35   754.4 2683.32
   774.9 2685.44   792.5 2685.92   848.5 2693.17   902.3 2695.08   950.7 2694.95
#Mann= 4 ,-1,0
       0     .05       0   554.1    .045       0   591.7     .05       0
     920     .06       0
#XS Ineff= 2 , 0
          461.41 2681.23
Permanent Ineff=
       F       F
Bank Sta=554.1,591.7
XS Rating Curve= 0 ,0
Exp/Cntr=0.3,0.1

Type RM Length L Ch R = 1 ,11270   ,270,267,264.1
XS GIS Cut Line= 2
2296678.58924508483080.3101696442297475.51108769483521.187898699
#Sta/Elev= 30
       0 2719.69    10.1 2718.31    20.1 2714.38      43 2702.21    90.1 2673.24
    98.9    2669   110.7 2666.79   184.3 2668.58   340.3 2669.69   436.1 2672.65
   500.1 2670.68   547.2 2671.01   572.8 2669.95   582.4 2671.12   586.9 2670.75
   595.3 2668.06   600.7 2666.48   605.2 2666.37     614 2666.66   619.9 2668.11
   628.1 2670.24   636.2 2670.46   742.4 2669.45   746.9 2669.92   751.5 2671.65
     762 2677.73   769.8 2681.08   802.3 2686.94   834.7 2689.77   910.7 2691.11
#Mann= 3 ,-1,0
       0     .05       0   595.3    .045       0   619.9     .05       0
#XS Ineff= 2 , 0
          544.19 2672.96
Permanent Ineff=
       F       F
Bank Sta=595.3,619.9
XS Rating Curve= 0 ,0
Exp/Cntr(USF)=0,0
Exp/Cntr=0.3,0.1