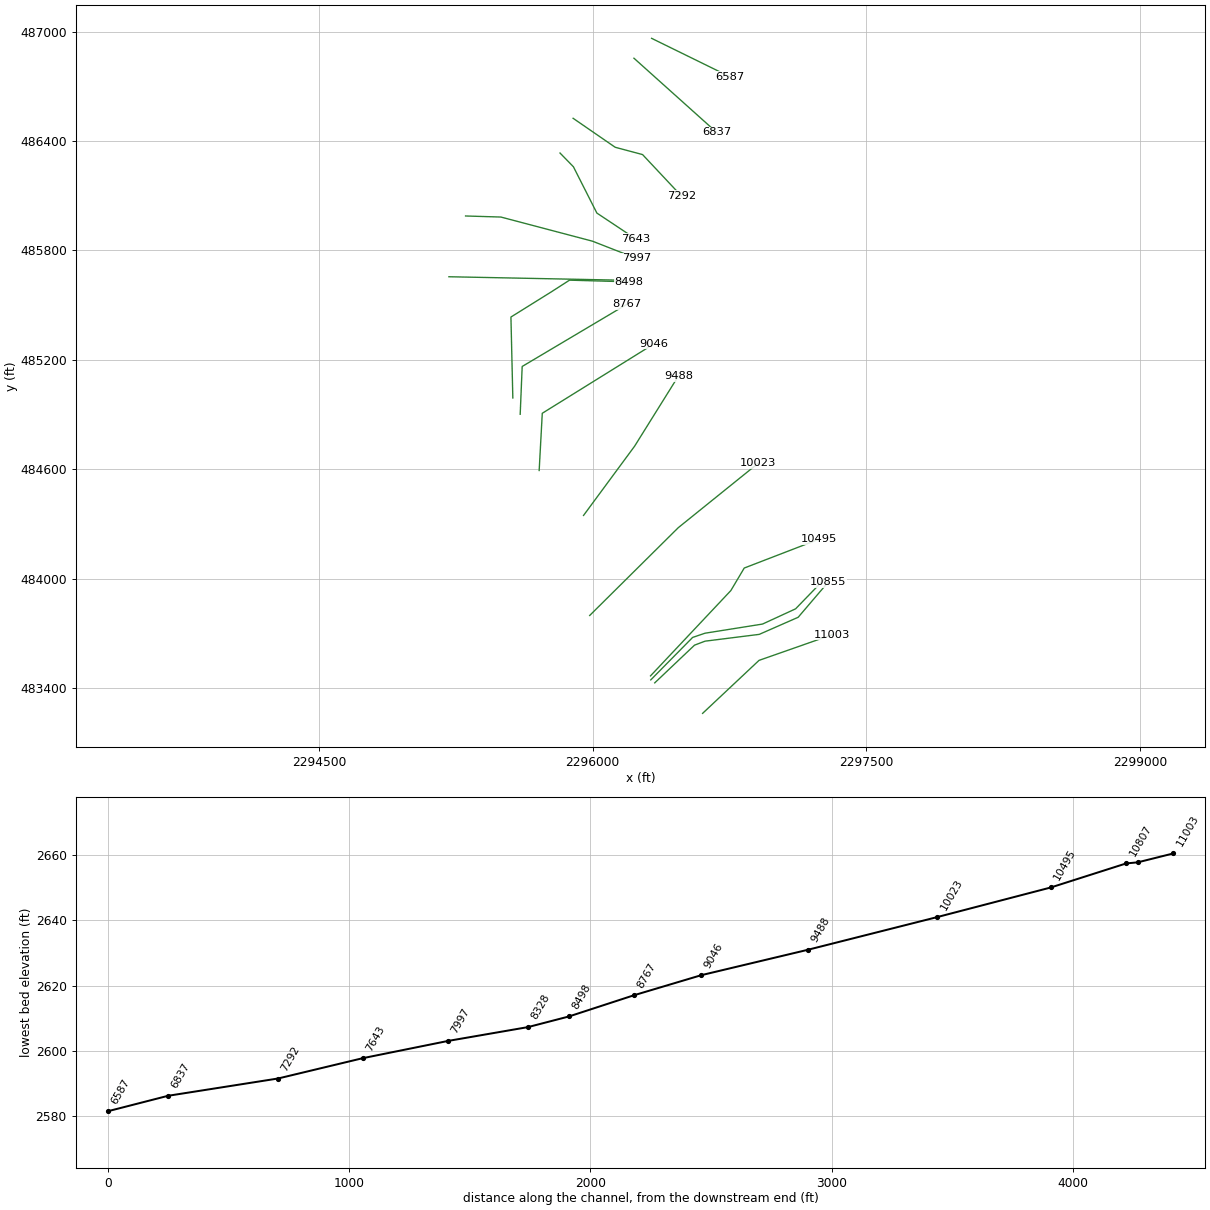
HEC-RAS study SHOCKRN.prj: SHOCKRN

--- SHOCKRN.g01 (geometry) --- (continued)

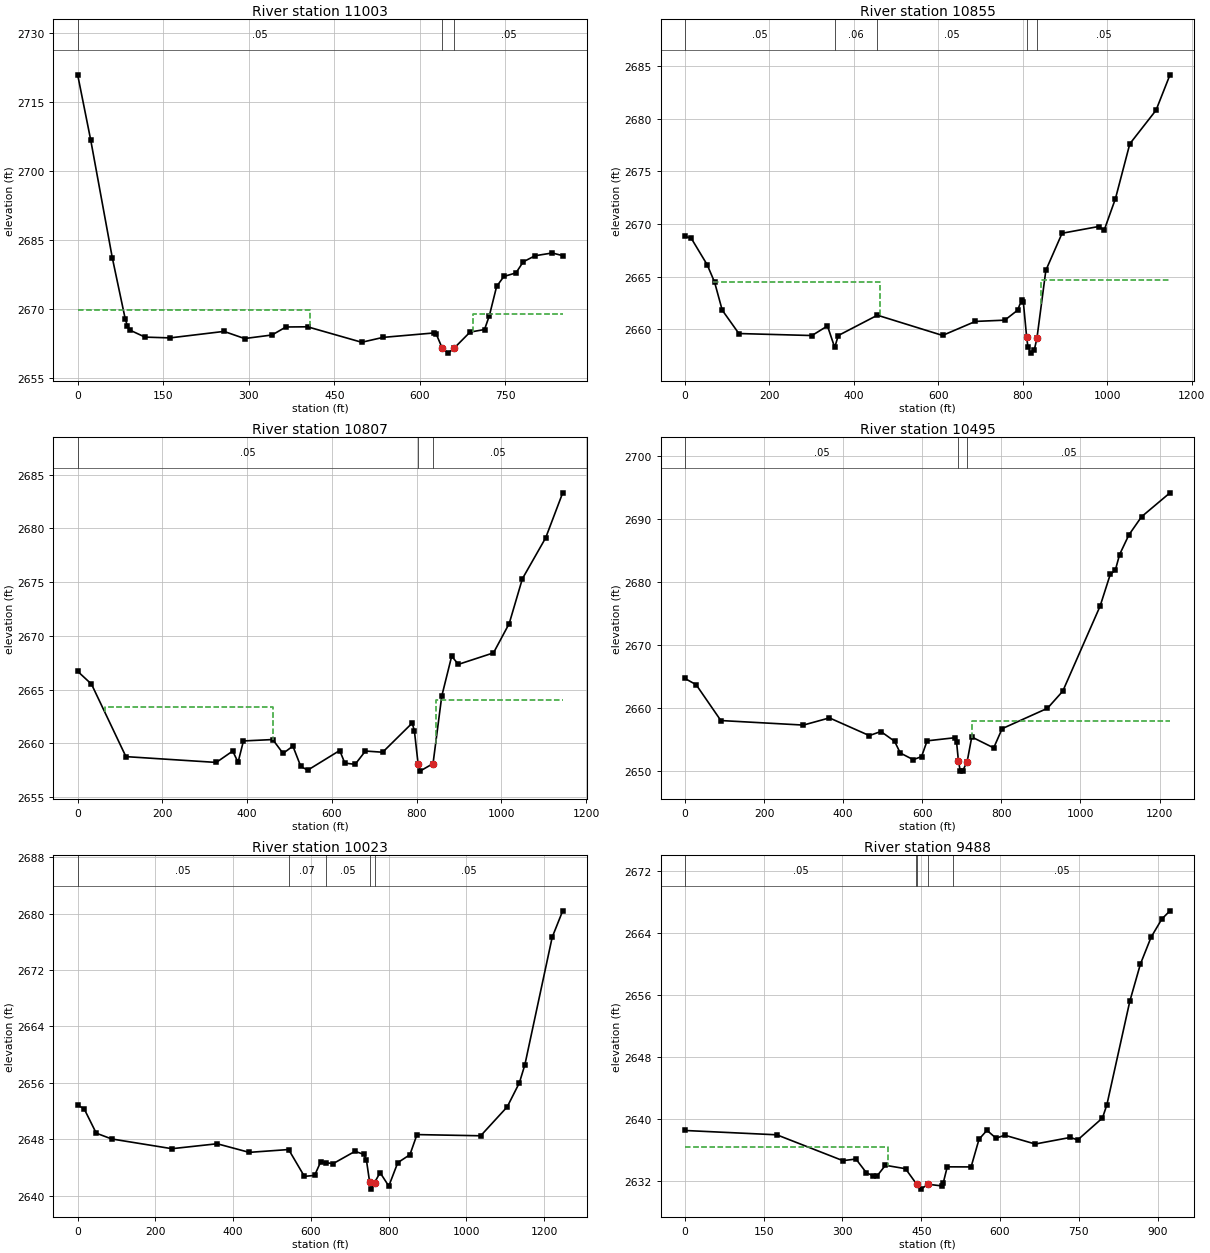
Type RM Length L Ch R = 1 ,11003   ,147,148.2,149.1
BEGIN DESCRIPTION:
structure xs 4
END DESCRIPTION:
XS GIS Cut Line= 3
 2296602.1141642483261.4407502952296911.23900881483552.036486154
2297313.47044722483693.226311065
#Sta/Elev= 30
       0 2720.95      23  2706.7    60.7 2681.22    83.3 2667.98    87.2 2666.37
    91.8 2665.47   118.1 2663.96     162 2663.79   256.6  2665.2   292.7 2663.65
   340.8 2664.42   365.2 2666.16   403.1  2666.2   498.1 2662.84   535.5  2663.9
   624.5 2664.86   628.7 2664.66   639.3 2661.56   649.9 2660.48   660.5  2661.6
   688.1 2665.05   713.5 2665.61     722 2668.64   734.7 2674.97   747.4 2677.14
   768.6 2677.91   781.4 2680.32   802.1 2681.64   832.2 2682.24   850.6 2681.66
#Mann= 3 ,-1,0
       0     .05       0   639.3    .045       0   660.5     .05       0
#XS Ineff= 2 , 0
          406.76 2669.94  692.96         2669.06
Permanent Ineff=
       F       F
Bank Sta=639.3,660.5
XS Rating Curve= 0 ,0
Exp/Cntr=0.5,0.3

Type RM Length L Ch R = 1 ,10855   ,51.2,47.7,48.2
BEGIN DESCRIPTION:
structure xs 3
END DESCRIPTION:
XS GIS Cut Line= 6
 2296339.8375643483428.7421371692296557.76561088483635.584743847
2296615.60671236483657.4358266282296912.52436662483694.711203137
2297125.89376319483788.5423233152297290.41956296483981.345994913
#Sta/Elev= 30
       0 2668.82    14.7 2668.66    52.7 2666.13    70.1 2664.49    88.3 2661.82
   127.7  2659.6   300.7 2659.41   337.5 2660.32   354.6 2658.28   363.1 2659.41
   455.7 2661.34     610 2659.42   687.7 2660.75   757.4 2660.87   787.9 2661.82
   797.1 2662.79   801.3 2662.58   809.1 2659.27   812.1 2658.35   818.8 2657.74
   827.3 2658.06   833.4 2659.13   854.6  2665.6     893 2669.12   979.6 2669.76
   992.7 2669.41  1019.4 2672.41  1053.4 2677.61  1115.5  2680.8  1148.5 2684.16
#Mann= 5 ,-1,0
       0     .05       0   354.6     .06       0   455.7     .05       0
   809.1    .045       0   833.4     .05       0
#XS Ineff= 3 ,-1
   65.78  462.46 2664.51  786.93     798 2660.19     844  1148.5 2664.72
Permanent Ineff=
       F       F       F
Bank Sta=809.1,833.4
XS Rating Curve= 0 ,0
Exp/Cntr(USF)=0,0
Exp/Cntr=0.5,0.3

Type RM Length L Ch R = 1 ,10807   ,296.8,312.4,322
BEGIN DESCRIPTION:
structure xs 2
END DESCRIPTION:
XS GIS Cut Line= 6
 2296318.1778713483445.207313652 2296547.4827484483678.001551598
2296615.60671236 483701.137992192296930.51937597483751.266946806
2297111.75482728483834.8152044982297269.85383799483998.055646451
#Sta/Elev= 30
       0  2666.7    32.6 2665.51   113.9 2658.76   327.2 2658.22     366 2659.28
   378.6 2658.23   391.3 2660.22   460.5 2660.35   484.8 2659.06     508 2659.74
   526.6 2657.85     543  2657.5   618.5 2659.33   630.6 2658.16   654.9 2658.04
   679.2 2659.28   719.9 2659.17   789.5 2661.88   794.7 2661.19   803.5 2658.11
     808 2657.41   838.8 2658.11   859.4 2664.39   882.8 2668.11   898.6 2667.35
   981.5 2668.42  1018.6 2671.15  1049.7 2675.32  1104.7 2679.13  1144.9 2683.32
#Mann= 3 ,-1,0
       0     .05       0   803.5    .045       0   838.8     .05       0
#XS Ineff= 3 ,-1
   63.79  460.47 2663.41  772.06   797.5    2659   844.8  1144.9    2664
Permanent Ineff=
       F       F       F
Bank Sta=803.5,838.8
XS Rating Curve= 0 ,0
Exp/Cntr(USF)=0,0
Exp/Cntr=0.5,0.3

Type RM Length L Ch R = 1 ,10495   ,478.4,471.6,464.7
XS GIS Cut Line= 4
2296316.68943787483467.0727449882296756.99607153483935.073113729
2296830.26146674484058.467463552 2297241.1050374484216.973531361
#Sta/Elev= 30
       0 2664.75    28.4 2663.76    90.8 2658.07   299.5 2657.35   365.4 2658.49
   466.2 2655.68   495.4 2656.33   530.1 2654.78   544.4 2652.92   577.2 2651.86
   598.2 2652.34   612.4 2654.85   682.2 2655.34   686.9 2654.59   691.5 2651.68
     696 2650.12   701.9 2650.04   713.6 2651.55   725.2 2655.46   780.7 2653.73
     802 2656.78   916.7 2660.02   955.3 2662.73  1049.7 2676.23  1075.4 2681.27
  1088.2 2681.94    1099 2684.42  1122.5 2687.54  1154.6 2690.43  1226.4 2694.22
#Mann= 3 ,-1,0
       0     .05       0   691.5    .045       0   713.6     .05       0
#XS Ineff= 2 , 0
                          724.85         2657.98
Permanent Ineff=
       F       F
Bank Sta=691.5,713.6
XS Rating Curve= 0 ,0
Exp/Cntr=0.3,0.1

Type RM Length L Ch R = 1 ,10023   ,530.1,535.6,539.5
XS GIS Cut Line= 3
2295983.39147163483798.3939119792296468.80944729484279.860130785
2296908.04455931484634.208881387
#Sta/Elev= 30
       0 2652.86    16.7 2652.33    47.8 2648.88    87.4 2648.06   242.5 2646.68
   358.9 2647.38   441.3 2646.16   542.8 2646.56   583.3 2642.76   609.6 2642.89
   624.8 2644.76   637.7 2644.71   657.2 2644.56   713.7 2646.31   736.8 2645.86
   743.1 2645.02751.35532641.891   755.9 2640.95763.80542641.871   778.1 2643.29
   800.5 2641.38   823.6  2644.7   854.9 2645.83     873 2648.68  1036.9 2648.51
  1105.2 2652.61  1136.5 2656.02  1150.6 2658.57  1220.9 2676.64    1248 2680.39
#Mann= 5 ,-1,0
       0     .05       0   542.8     .07       0   637.7     .05       0
751.3553    .045       0763.8054     .05       0
Bank Sta=751.3553,763.8054
XS Rating Curve= 0 ,0
Exp/Cntr=0.3,0.1

Type RM Length L Ch R = 1 ,9488    ,446.9,441.5,434.9
XS GIS Cut Line= 3
     2295949.635      484347.068     2296229.058      484726.197
     2296468.666      485110.243
#Sta/Elev= 30
       0 2638.52     175 2637.96   300.8 2634.62   325.6 2634.83   345.5 2633.06
     358 2632.66   365.4 2632.61   381.8 2634.02     420 2633.58     441  2631.6
   449.6 2630.94   462.7 2631.57   488.6 2631.36     492 2631.78   499.5 2633.82
   544.9 2633.81     560 2637.39   575.1 2638.54   592.4 2637.52     609 2637.91
     667 2636.77   733.8 2637.62   747.9  2637.3   795.1 2640.14   803.5 2641.86
   847.1 2655.22   867.3 2660.03   887.7 2663.51   908.2 2665.86   923.6 2666.91
#Mann= 5 ,-1,0
       0     .05       0     440     .07       0     441    .045       0
   462.7     .07       0  510.97     .05       0
#XS Ineff= 2 , 0
          386.48 2636.33
Permanent Ineff=
       F       F
Bank Sta=441,462.7
XS Rating Curve= 0 ,0
Exp/Cntr=0.3,0.1

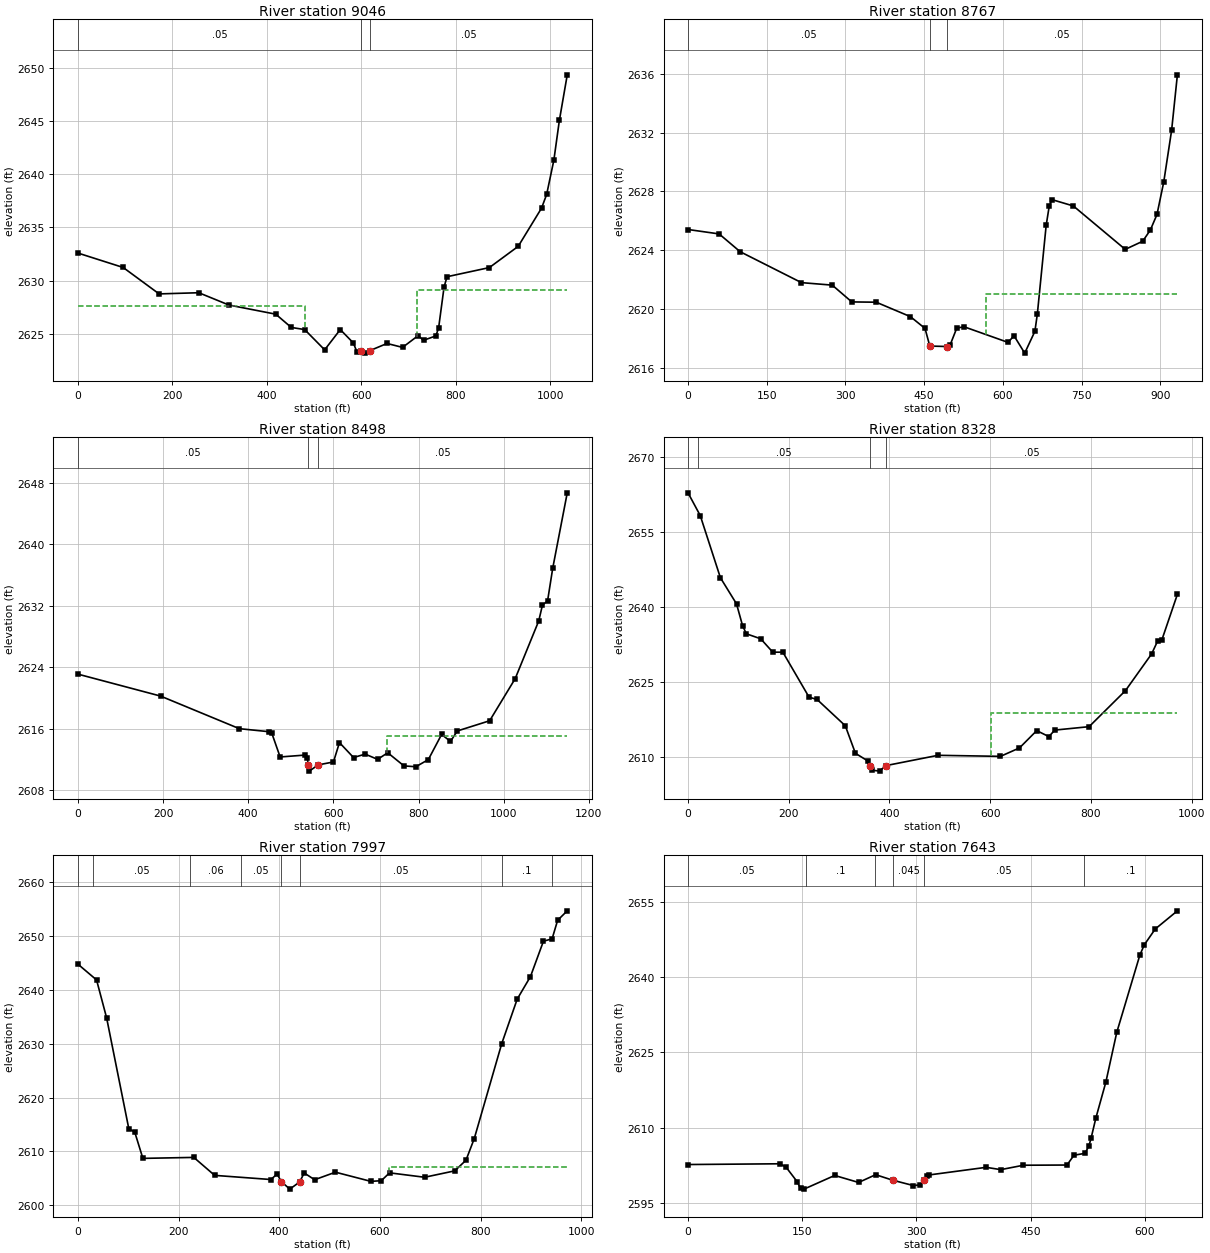
Type RM Length L Ch R = 1 ,9046    ,280,278.9,276.7
XS GIS Cut Line= 3
2295706.48000136484593.5381081062295723.48189716484907.290906508
 2296336.1240374485288.245090769
#Sta/Elev= 30
       0 2632.59    95.8 2631.23   171.9 2628.74   255.9 2628.85   319.7 2627.69
   418.7 2626.83   451.6 2625.58   479.9 2625.38   522.2 2623.47   555.3 2625.38
   582.9 2624.12   590.5 2623.28  599.46  2623.4   607.1 2623.16   618.1  2623.4
   654.2 2624.07   687.1  2623.7   720.1 2624.81   731.4 2624.37   757.5 2624.78
   763.4 2625.54     775 2629.41   781.3 2630.36   870.8 2631.22   931.8 2633.22
   981.2 2636.82     992 2638.11  1007.3 2641.35  1018.9 2645.08  1035.6 2649.38
#Mann= 3 ,-1,0
       0     .05       0  599.46    .045       0   618.1     .05       0
#XS Ineff= 2 , 0
          480.06 2627.64  717.61         2629.07
Permanent Ineff=
       F       F
Bank Sta=599.46,618.1
XS Rating Curve= 0 ,0
Exp/Cntr=0.3,0.1

Type RM Length L Ch R = 1 ,8767    ,268.6,269.6,270.1
XS GIS Cut Line= 3
2295602.49237776484901.8802427252295613.36237899485163.966287179
2296189.63113077485506.474472181
#Sta/Elev= 30
       0 2625.41    59.3 2625.11    99.4  2623.9   216.2  2621.8   274.9 2621.63
   312.1 2620.49   358.7 2620.47   423.8 2619.49   451.7 2618.69   460.8 2617.49
   492.9 2617.46   499.6 2617.57   512.2 2618.71   526.2  2618.8   609.9 2617.74
   621.3 2618.19   641.7 2617.01   661.1 2618.49   665.8 2619.67   682.6 2625.69
   688.4 2626.99   693.7 2627.44   734.4 2627.01   833.3 2624.06   866.5 2624.61
   881.1 2625.37   893.8 2626.43   906.7 2628.64   921.7 2632.15   932.7 2635.92
#Mann= 3 ,-1,0
       0     .05       0   460.8    .045       0   492.9     .05       0
#XS Ineff= 2 , 0
                          568.72            2621
Permanent Ineff=
       F       F
Bank Sta=460.8,492.9
XS Rating Curve= 0 ,0
Exp/Cntr(USF)=0,0
Exp/Cntr=0.3,0.1

Type RM Length L Ch R = 1 ,8498    ,178.7,169.7,155.9
XS GIS Cut Line= 5
2295562.11143743484991.2147315352295551.71280993485435.065704922
 2295773.0118486485573.1226549562295872.69917357485637.300798651
2296198.31280116485628.154119206
#Sta/Elev= 30
       0 2623.12     194 2620.27   379.1 2616.03     448 2615.64   455.5 2615.42
   474.9 2612.35   534.1  2612.6   538.8  2612.2540.89392611.355   543.5 2610.51
   564.1 2611.32   600.1  2611.7   614.2 2614.22   647.2 2612.28   674.7 2612.72
   703.8 2612.04   727.6  2612.9   765.7 2611.19   793.6 2611.08   822.9 2612.01
   854.1 2615.28   874.9 2614.37   890.9 2615.73   966.9 2617.06  1026.9 2622.54
  1082.1 2630.03  1090.9  2632.1  1102.9 2632.64    1115 2636.89  1149.1 2646.69
#Mann= 3 ,0,0
       0     .05       0540.8939    .045       0   564.1     .05       0
#XS Ineff= 2 , 0
                          726.05         2615.13
Permanent Ineff=
       F       F
Bank Sta=540.8939,564.1
XS Rating Curve= 0 ,0
Exp/Cntr=0.3,0.1

Type RM Length L Ch R = 1 ,8328    ,332,330.7,322.3
XS GIS Cut Line= 2
2295211.88929675485656.0369615392296183.40116735485636.641987716
#Sta/Elev= 30
       0 2662.84    24.3 2658.29    64.3 2645.88    96.3 2640.66   108.3 2636.31
   115.8 2634.68   144.3 2633.69   168.3 2631.01   188.3 2631.01   240.3 2622.03
   256.3 2621.56   312.3 2616.31   332.4 2610.81   356.4 2609.32   360.4 2608.28
   364.4 2607.45   380.4 2607.25   392.4 2608.34   496.4 2610.41   620.4  2610.2
   658.1 2611.88   692.4 2615.34   716.4 2614.15   728.4 2615.45   796.4 2616.13
   868.5 2623.32   920.5 2630.66   932.5 2633.24   940.5 2633.35   971.7 2642.56
#Mann= 4 ,-1,0
       0     .06       0      20     .05       0   360.4    .045       0
   392.4     .05       0
#XS Ineff= 2 , 0
                          601.33         2618.95
Permanent Ineff=
       F       F
Bank Sta=360.4,392.4
XS Rating Curve= 0 ,0
Exp/Cntr(USF)=0,0
Exp/Cntr=0.3,0.1

Type RM Length L Ch R = 1 ,7997    ,371,354.5,331.2
XS GIS Cut Line= 4
2295303.12811861485989.2885130032295496.69711725485983.485302004
2295998.09289302485851.2103731762296240.25157185 485756.47618613
#Sta/Elev= 30
       0 2644.73    37.1  2641.8    57.1 2634.76   101.1 2614.25   113.1 2613.55
   129.1 2608.72   230.3  2608.9   271.7 2605.57   383.4  2604.8   395.8 2605.82
   404.1 2604.42     421 2603.02   440.6 2604.35   449.6 2606.02   470.3 2604.76
   511.7 2606.16     582 2604.46   602.7 2604.58   619.2 2606.04   688.8 2605.22
   748.8 2606.41     771 2608.38   787.5  2612.4     842 2629.98   872.8 2638.25
   899.1 2642.42   924.9 2648.98   942.1 2649.42   953.1 2652.86   972.2 2654.61
#Mann= 8 ,-1,0
       0     .06       0      30     .05       0  223.66     .06       0
  323.66     .05       0   404.1    .045       0   440.6     .05       0
  842.21      .1       0  942.21     .05       0
#XS Ineff= 2 , 0
                          618.77         2607.07
Permanent Ineff=
       F       F
Bank Sta=404.1,440.6
XS Rating Curve= 0 ,0
Exp/Cntr=0.3,0.1

Type RM Length L Ch R = 1 ,7643    ,335.7,350.6,368.5
XS GIS Cut Line= 4
2295820.72317734486334.5247781162295894.11317189486259.248131129
2296022.64895296486005.350291987 2296233.1384336485865.085884155
#Sta/Elev= 30
       0 2602.63   120.9 2602.78     129 2602.06   143.3 2599.21   147.8 2597.85
   152.3 2597.72   192.6 2600.45     224 2599.05   246.4  2600.6268.8673  2599.5
   295.8 2598.44   304.7 2598.56310.56732599.501   313.7 2600.38   316.6 2600.55
   391.5 2602.07   410.8 2601.61   440.5 2602.49   497.7 2602.53   506.9 2604.49
   521.3 2604.86   526.5 2606.33   529.4 2607.92   535.7 2611.95   548.7 2619.05
   563.1 2629.02   593.4 2644.43   599.2 2646.48   613.6 2649.64   642.7 2653.27
#Mann= 6 ,-1,0
       0     .05       0  155.13      .1       0  245.13     .05       0
268.8673    .045       0310.5673     .05       0  519.71      .1       0
Bank Sta=268.8673,310.5673
XS Rating Curve= 0 ,0
Exp/Cntr=0.3,0.1

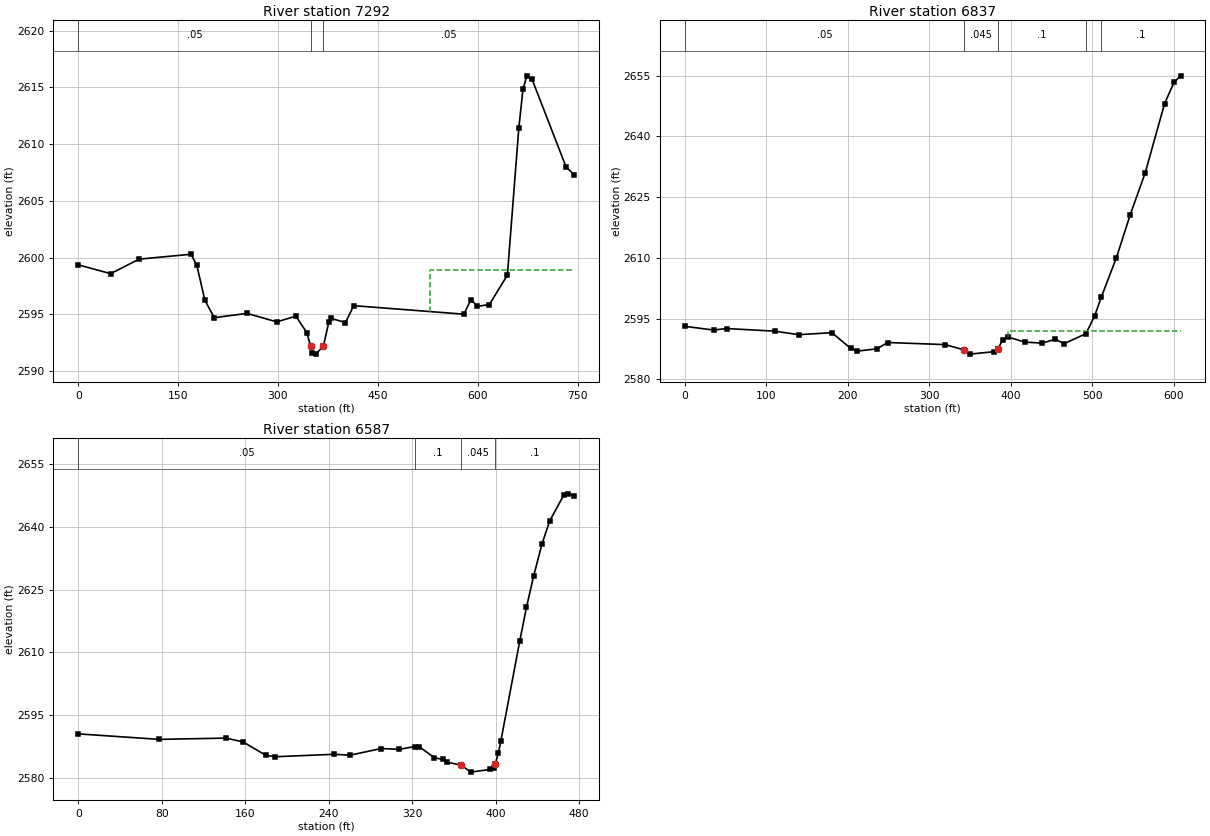
Type RM Length L Ch R = 1 ,7292    ,453.4,455.2,445.9
XS GIS Cut Line= 4
2295892.38062745486525.0985339612296123.02748363486366.137748086
2296272.99250732486326.0728270812296484.79222648486100.312358882
#Sta/Elev= 30
       0 2599.37    48.7 2598.59    91.5 2599.87   169.5  2600.3   178.1 2599.33
   190.2 2596.26   204.3 2594.71   253.6 2595.09   298.2 2594.34   326.8 2594.84
   343.4  2593.4  349.02 2592.21   351.7 2591.57     357  2591.5   368.3 2592.23
   376.5 2594.34   379.9 2594.65   401.4 2594.28   413.8 2595.77   579.2 2595.02
   590.1 2596.31   599.5 2595.71   617.6 2595.87   644.6 2598.46   661.8 2611.43
     668 2614.82   673.8 2616.02   681.6 2615.73   732.7    2608   744.9 2607.29
#Mann= 3 ,0,0
       0     .05       0  349.02    .045       0   368.3     .05       0
#XS Ineff= 2 , 0
                          528.68         2598.89
Permanent Ineff=
       F       F
Bank Sta=349.02,368.3
XS Rating Curve= 0 ,0
Exp/Cntr=0.3,0.1

Type RM Length L Ch R = 1 ,6837    ,244.7,249.9,256.2
XS GIS Cut Line= 2
2296225.85610848486854.5737161382296678.55077612486448.300678019
#Sta/Elev= 30
       0 2593.08    35.4 2592.16    51.5 2592.53   110.6 2591.88   139.8 2591.01
   180.5 2591.51   203.7 2587.61   211.7 2586.96   235.6 2587.51   249.1 2589.08
   319.5 2588.56   342.72587.253   349.4 2586.21   379.4 2586.81   384.2 2587.45
   390.1 2589.79   396.4 2590.44     417 2589.19   438.5 2588.92   454.6 2589.89
   465.3 2588.78   492.2 2591.27     503 2595.72   511.1 2600.34   529.5    2610
   546.5 2620.64     565 2631.07   588.6 2648.08   600.3 2653.36   608.3 2654.95
#Mann= 5 ,-1,0
       0     .05       0   342.7    .045       0   384.2      .1       0
   492.2     .05       0   511.1      .1       0
#XS Ineff= 2 , 0
                          396.81         2591.97
Permanent Ineff=
       F       F
Bank Sta=342.7,384.2
XS Rating Curve= 0 ,0
Exp/Cntr(USF)=0,0
Exp/Cntr=0.3,0.1

Type RM Length L Ch R = 1 ,6587    ,254.2,262,270.7
XS GIS Cut Line= 2
2296322.64016355486963.5561290622296749.27300749486754.161531361
#Sta/Elev= 30
       0 2590.59    77.6 2589.28   141.6 2589.58   157.7 2588.69   179.9 2585.47
   188.9 2585.14     245 2585.72   260.7 2585.52   289.9 2587.08   307.8 2586.91
   322.5 2587.57     327  2587.5   341.3  2584.9   349.3  2584.5   353.7 2583.81
   367.1 2583.15     376 2581.47   394.5  2582.1   398.3 2582.57  399.58 2583.38
   402.7 2586.14   404.9 2588.79     423 2612.63   429.5 2620.76   436.3 2628.15
   444.4 2635.89   451.7 2641.33   465.1 2647.46   469.6 2647.82   475.2 2647.39
#Mann= 4 ,-1,0
       0     .05       0   322.5      .1       0   367.1    .045       0
  399.58      .1       0
Bank Sta=367.1,399.58
XS Rating Curve= 0 ,0
Exp/Cntr=0.3,0.1