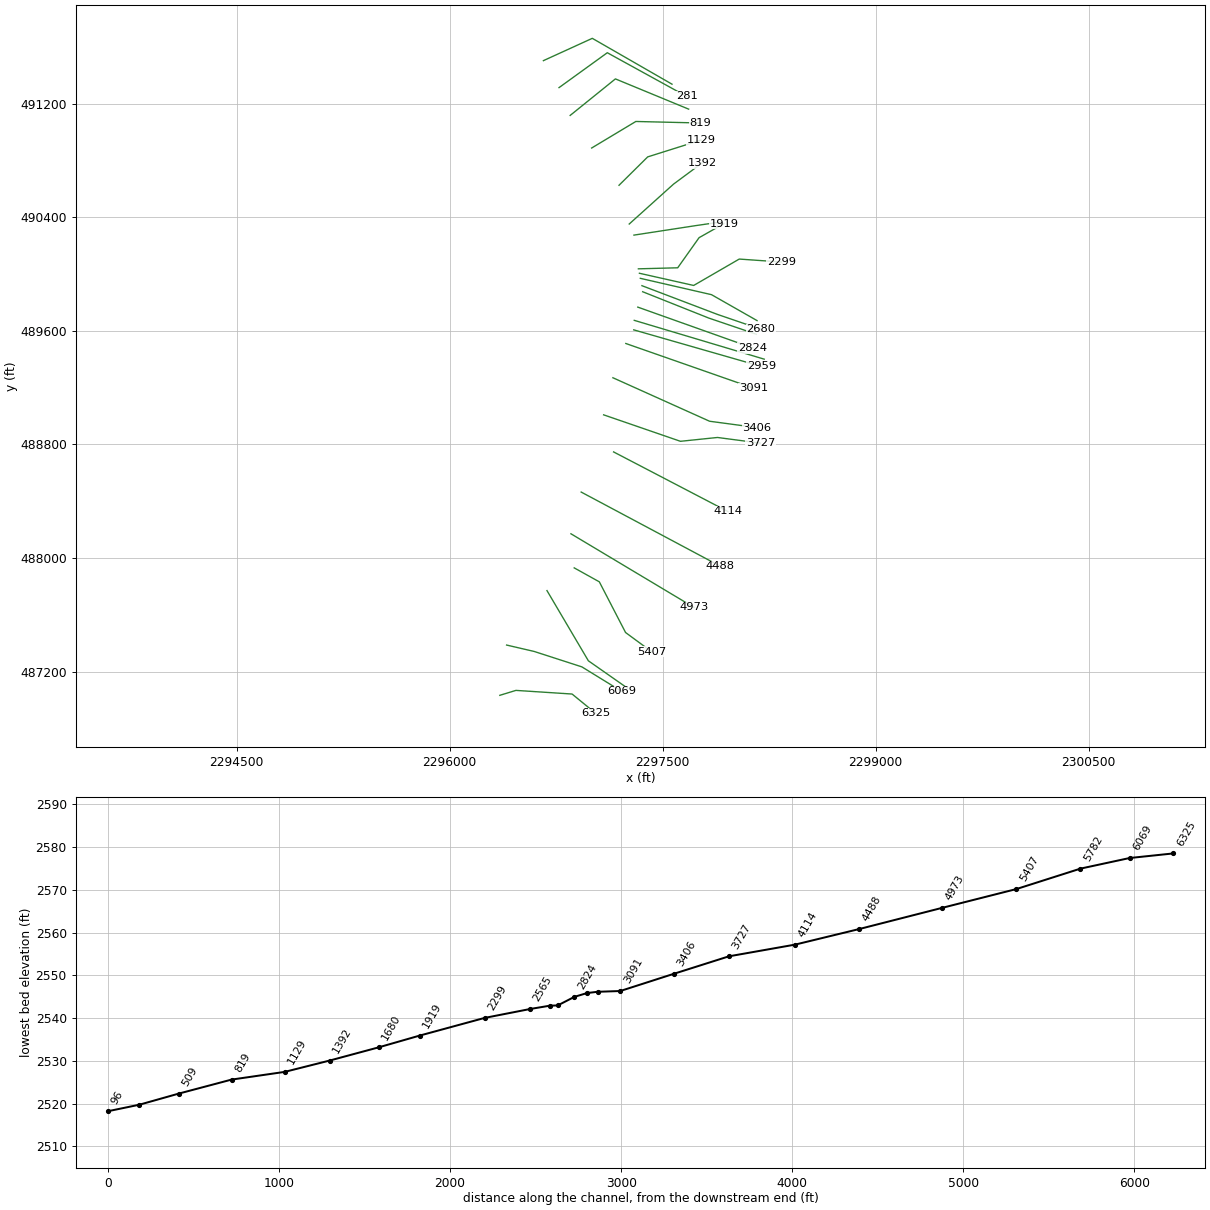
HEC-RAS study SHOCKRN.prj: SHOCKRN

--- SHOCKRN.g01 (geometry) --- (continued)

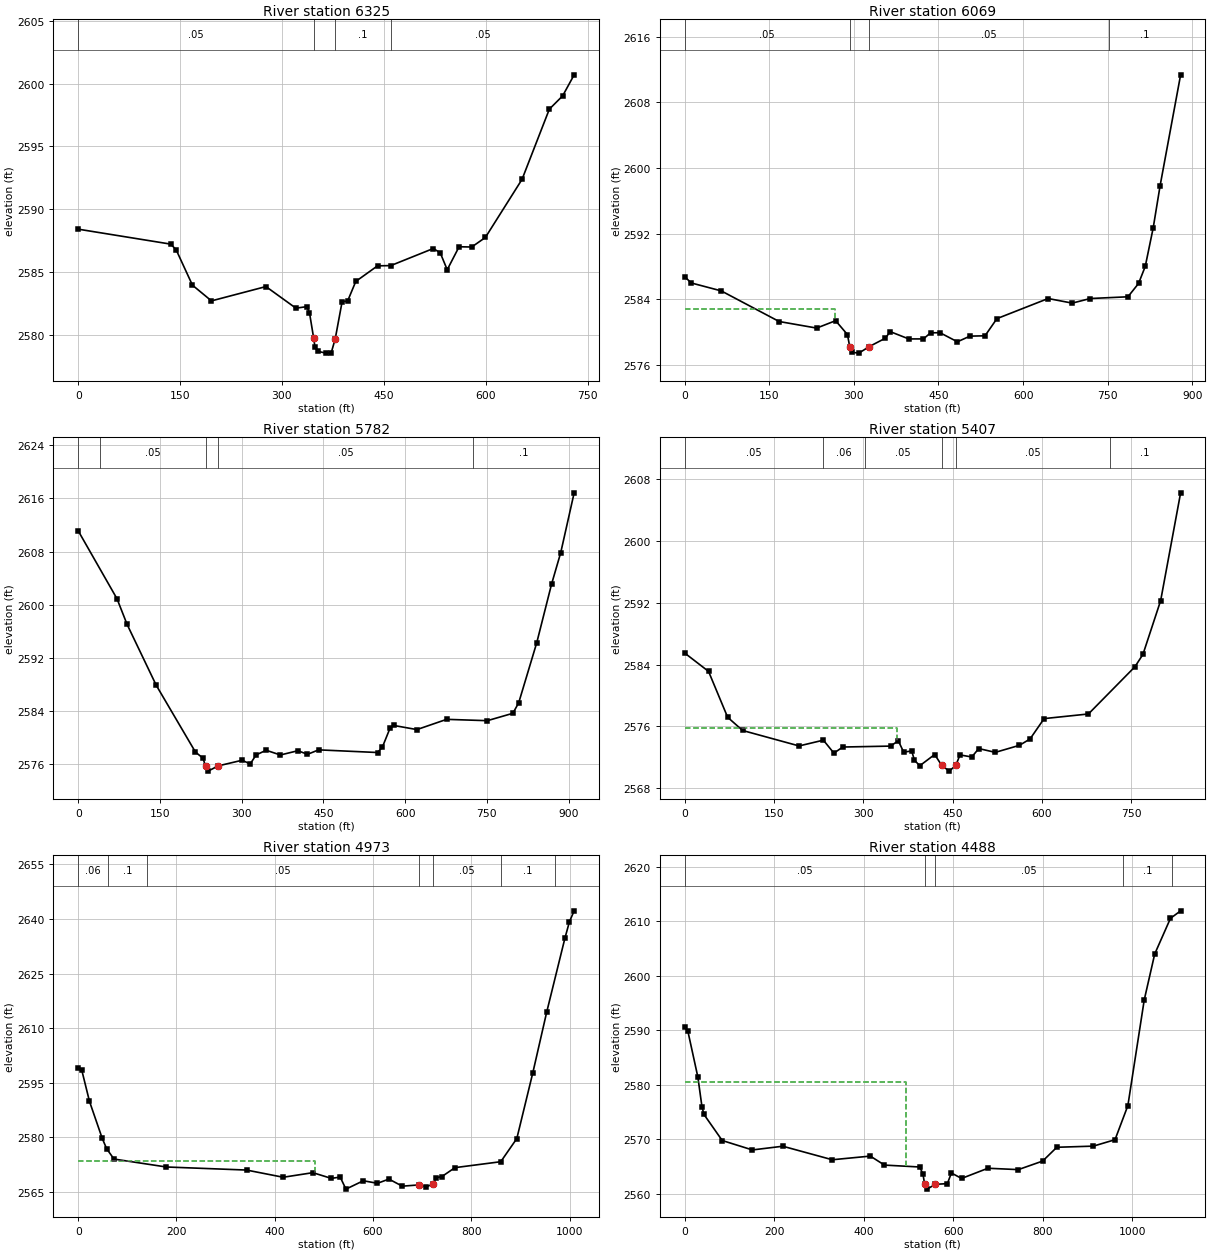
Type RM Length L Ch R = 1 ,6325    ,262.9,256.4,251.5
XS GIS Cut Line= 4
2296353.32235514487033.1771481032296466.71775073487067.893732031
2296862.10822476487042.2359564952297029.03586601486906.049437435
#Sta/Elev= 30
       0 2588.41   136.1 2587.22   144.1 2586.78   168.2 2583.95   196.2  2582.7
   276.4 2583.84   320.5 2582.12   336.5 2582.24   340.5 2581.76  346.69 2579.73
   348.5 2579.06   352.5 2578.69   364.6 2578.54   372.6 2578.58   378.5  2579.7
   388.6 2582.65   396.6 2582.68   408.7 2584.25   440.7 2585.49   460.2 2585.51
   522.8 2586.87     533 2586.53   543.3 2585.18   560.8 2587.01   579.4 2586.99
   599.5 2587.75   653.5 2592.38   693.7 2597.97   713.2 2599.02   730.2  2600.7
#Mann= 4 ,-1,0
       0     .05       0  346.69    .045       0   378.5      .1       0
   460.2     .05       0
Bank Sta=346.69,378.5
XS Rating Curve= 0 ,0
Exp/Cntr=0.3,0.1

Type RM Length L Ch R = 1 ,6069    ,295.6,287.1,271
XS GIS Cut Line= 4
   2296401.04699487387.1529364392296595.42165448487342.022595533
2296931.04286059  487233.4812693 2297209.5370529487062.100227879
#Sta/Elev= 30
       0 2586.78    11.4 2586.01    64.8 2585.04   167.5 2581.31     234 2580.51
   267.6 2581.41   288.6 2579.72   292.7 2578.21     297 2577.56   308.8 2577.46
   327.42578.263   355.9 2579.28   364.3 2580.08   397.3 2579.19   423.3 2579.19
   435.9 2579.93   452.6 2579.95   483.5 2578.84   505.8 2579.53   532.5 2579.57
   553.6 2581.66   644.4 2584.11   687.1 2583.55   719.1 2584.11   785.9 2584.32
   804.7 2585.94   816.6 2588.02   830.7 2592.72   842.9 2597.84   879.3 2611.35
#Mann= 4 ,-1,0
       0     .05       0   292.7    .045       0   327.4     .05       0
  752.28      .1       0
#XS Ineff= 2 , 0
          267.04 2582.89
Permanent Ineff=
       F       F
Bank Sta=292.7,327.4
XS Rating Curve= 0 ,0
Exp/Cntr(USF)=0,0
Exp/Cntr=0.3,0.1

Type RM Length L Ch R = 1 ,5782    ,374.1,374.7,372.2
XS GIS Cut Line= 3
2296685.39670122487770.4751990852296976.74447164487276.326529655
2297252.38231326487083.522858057
#Sta/Elev= 30
       0 2611.13    71.2 2600.91    89.7 2597.05   143.2 2587.89   215.1 2577.85
     229 2576.92   233.7  2575.7   238.3 2574.98   256.9 2575.77   300.9 2576.62
   315.5 2576.05   326.5 2577.42   344.8 2578.12     371 2577.41   403.1 2578.05
   420.7 2577.51   441.2 2578.18   549.2 2577.78     558 2578.57   572.6 2581.53
   579.1 2581.85   621.5 2581.23     676 2582.77   750.7 2582.57   797.5 2583.68
   808.2 2585.25   841.4 2594.31   868.5  2603.1   885.4 2607.86     910 2616.85
#Mann= 5 ,-1,0
       0     .06       0      40     .05       0   233.7    .045       0
   256.9     .05       0  723.64      .1       0
Bank Sta=233.7,256.9
XS Rating Curve= 0 ,0
Exp/Cntr(USF)=0,0
Exp/Cntr=0.3,0.1

Type RM Length L Ch R = 1 ,5407    ,417.7,434.3,439.2
XS GIS Cut Line= 4
 2296877.0849831487930.5584534712297053.90038406487832.270706766
2297238.71806329487475.4015386882297423.19066714 487339.67529509
#Sta/Elev= 30
       0 2585.49    40.1 2583.11    72.2 2577.17    97.4 2575.46   192.2 2573.46
     233 2574.21   250.7 2572.53   265.6 2573.32   345.8 2573.44   358.9 2574.13
   367.9 2572.66   381.4 2572.81     386 2571.61     395  2570.9     420 2572.35
   431.8 2570.95   444.5  2570.2   455.6 2570.95   462.5  2572.3   482.3 2572.03
   494.1 2573.12   521.9 2572.63   562.4 2573.54   580.2 2574.36   603.9    2577
   678.3  2577.6   756.4 2583.71   769.9 2585.31   799.7 2592.29   833.2 2606.23
#Mann= 6 ,-1,0
       0     .05       0   232.3     .06       0   302.3     .05       0
   431.8    .045       0   455.6     .05       0  714.18      .1       0
#XS Ineff= 2 , 0
          357.18 2575.73
Permanent Ineff=
       F       F
Bank Sta=431.8,455.6
XS Rating Curve= 0 ,0
Exp/Cntr=0.3,0.1

Type RM Length L Ch R = 1 ,4973    ,478.3,484.2,484.6
XS GIS Cut Line= 2
2296854.19623274488170.5742107612297720.34776802487652.254017734
#Sta/Elev= 30
       0 2599.04       7 2598.61    22.9 2589.92    48.9 2579.73    57.9 2576.89
    72.8 2574.06   179.4 2571.88   342.6 2571.04   417.2 2569.06   477.6 2570.32
   515.1 2568.75   533.2 2569.11   544.9  2565.8   580.3  2568.1   609.1  2567.4
   632.4 2568.56   659.6 2566.61   693.6 2566.96   708.2 2566.45   721.4 2567.11
   728.6 2568.92   740.3 2569.26   766.8  2571.7     860 2573.33   892.7 2579.69
   925.3 2597.78   953.5 2614.41   990.5 2634.67   999.8 2639.25  1009.4 2642.24
#Mann= 7 ,-1,0
       0     .06       0      60      .1       0     140     .05       0
   693.6    .045       0   721.4     .05       0     860      .1       0
     970     .12       0
#XS Ineff= 2 , 0
          482.53 2573.49
Permanent Ineff=
       F       F
Bank Sta=693.6,721.4
XS Rating Curve= 0 ,0
Exp/Cntr=0.3,0.1

Type RM Length L Ch R = 1 ,4488    ,373.3,374.3,374
XS GIS Cut Line= 2
2296926.12014135488464.3579528822297904.25866206487942.938188472
#Sta/Elev= 30
       0 2590.52     6.9 2589.91    29.5  2581.4    38.6 2575.98    43.1 2574.55
    83.9 2569.77   151.3 2568.04   219.3 2568.72   329.9 2566.24   414.9 2566.91
   446.5 2565.26   525.5 2564.91   532.7 2563.56   536.1 2561.83   541.7 2560.85
   560.3 2561.73   587.1 2561.86   596.1 2563.81   618.9 2562.81   677.7 2564.68
   745.7 2564.43   800.1    2566   831.7 2568.53   913.4 2568.74   961.8 2569.92
   990.5 2576.17  1027.1 2595.57  1050.5 2603.99  1085.7 2610.53  1108.4 2611.91
#Mann= 5 ,-1,0
       0     .05       0   536.1    .045       0   560.3     .05       0
     980      .1       0    1090     .12       0
#XS Ineff= 2 , 0
          494.35 2580.49
Permanent Ineff=
       F       F
Bank Sta=536.1,560.3
XS Rating Curve= 0 ,0
Exp/Cntr=0.3,0.1

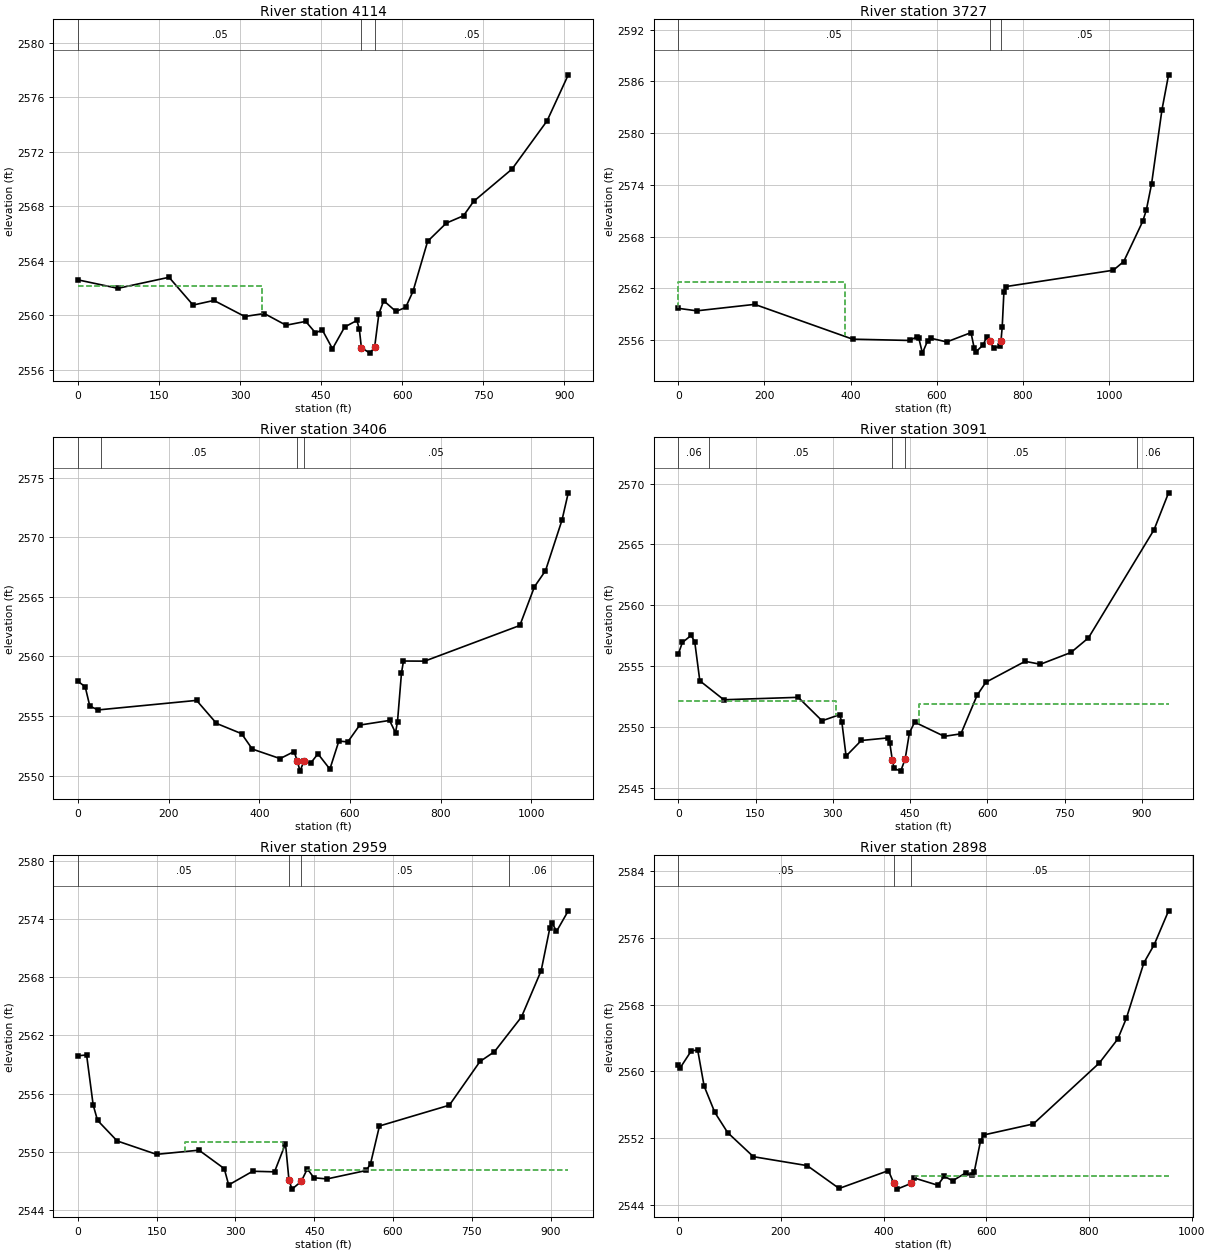
Type RM Length L Ch R = 1 ,4114    ,380.2,387.1,400.3
XS GIS Cut Line= 2
 2297154.5521247488746.9322908182297958.93117182488327.552445979
#Sta/Elev= 30
       0 2562.59      74 2561.97   168.5 2562.78     213 2560.74   251.6 2561.08
   308.6  2559.9   344.7 2560.12     385 2559.26   421.4 2559.54   439.4  2558.7
   452.1 2558.91   470.9 2557.53   493.5 2559.13   516.1 2559.61   520.6 2558.96
   524.4 2557.61   540.2 2557.21   548.9 2557.65   556.7 2560.09   565.7 2561.06
   588.3 2560.27   606.3 2560.57   619.8 2561.74   646.9 2565.42   681.5 2566.76
   713.3  2567.3   731.9 2568.35   803.1 2570.73   867.9 2574.27   907.1 2577.65
#Mann= 3 ,-1,0
       0     .05       0   524.4    .045       0   548.9     .05       0
#XS Ineff= 2 , 0
          339.66 2562.15
Permanent Ineff=
       F       F
Bank Sta=524.4,548.9
XS Rating Curve= 0 ,0
Exp/Cntr=0.3,0.1

Type RM Length L Ch R = 1 ,3727    ,332.5,321.4,327
XS GIS Cut Line= 4
2297084.33567507489008.0961565612297625.12829519488821.751093926
2297885.88163207488848.7038537312298187.38531605488809.032316365
#Sta/Elev= 30
       0 2559.67    43.1 2559.38   177.5 2560.13   404.9 2556.09   537.3 2555.94
   554.1 2556.37   558.3 2556.24   566.8 2554.47   579.1 2555.92   587.1 2556.19
   623.3 2555.77   679.6 2556.85   687.2 2555.02   691.7 2554.65   707.8 2555.42
   715.8 2556.34  724.45 2555.86   731.9 2555.06     748 2555.27   749.2  2555.9
     752 2557.46     756 2561.57     760 2562.19  1009.9 2564.09  1034.1  2565.1
  1078.2 2569.76  1086.6 2571.08  1098.7 2574.09  1122.9 2582.72  1138.2 2586.77
#Mann= 3 ,-1,0
       0     .05       0  724.45    .045       0   749.2     .05       0
#XS Ineff= 2 , 0
          386.71 2562.68
Permanent Ineff=
       F       F
Bank Sta=724.45,749.2
XS Rating Curve= 0 ,0
Exp/Cntr(USF)=0,0
Exp/Cntr=0.3,0.1

Type RM Length L Ch R = 1 ,3406    ,313.7,314.3,313.3
XS GIS Cut Line= 3
2297149.57789856 489269.222149812297830.34147976488962.957881345
2298161.99553214488918.525759495
#Sta/Elev= 30
       0 2557.92      16 2557.46    26.2 2555.84    44.3 2555.52   261.6 2556.32
   305.5 2554.39   360.8 2553.53   384.4 2552.24   445.8 2551.44   476.6 2552.03
   483.5 2551.25   489.7 2550.39   498.1 2551.21   513.3 2551.07   529.2 2551.84
   555.5 2550.56   575.3 2552.91     595 2552.84   621.3 2554.25   687.1 2554.64
   700.2 2553.61   704.6 2554.54   713.4 2558.63   717.8 2559.62   764.5 2559.61
   974.3  2562.6  1006.6 2565.85  1030.9 2567.19  1067.2 2571.42  1081.1 2573.72
#Mann= 4 ,-1,0
       0     .06       0      50     .05       0   483.5    .045       0
   498.1     .05       0
Bank Sta=483.5,498.1
XS Rating Curve= 0 ,0
Exp/Cntr(USF)=0,0
Exp/Cntr=0.3,0.1

Type RM Length L Ch R = 1 ,3091    ,132,132.7,133.9
BEGIN DESCRIPTION:
structure xs 4
END DESCRIPTION:
XS GIS Cut Line= 2
2297240.62299448 489510.334809632298138.94528659489196.136233692
#Sta/Elev= 30
       0 2555.96       8 2556.93      25 2557.51      32    2557    41.9 2553.78
    88.5 2552.22   232.9 2552.42   279.2 2550.49   313.1 2550.99   317.6 2550.38
   325.8 2547.59   355.3 2548.87   406.3 2549.08   410.6 2548.67   415.4  2547.3
     419 2546.57   431.8 2546.35   440.5 2547.35   448.7  2549.5   458.9 2550.38
   516.5 2549.21   548.7 2549.42   580.1 2552.59   597.1 2553.66   673.3 2555.38
     703 2555.14   762.3 2556.11   796.2 2557.31   923.6 2566.21   951.7 2569.24
#Mann= 5 ,-1,0
       0     .06       0      60     .05       0   415.4    .045       0
   440.5     .05       0     890     .06       0
#XS Ineff= 2 , 0
          307.04  2552.1  467.04         2551.85
Permanent Ineff=
       F       F
Bank Sta=415.4,440.5
XS Rating Curve= 0 ,0
Exp/Cntr(USF)=0,0
Exp/Cntr=0.5,0.3

Type RM Length L Ch R = 1 ,2959    ,60.9,60.8,61.8
BEGIN DESCRIPTION:
structure xs 3
END DESCRIPTION:
XS GIS Cut Line= 2
2297296.34147041489606.407446574 2298193.7998046489348.983248555
#Sta/Elev= 30
       0  2559.9    16.5 2559.98      29 2554.84    37.3 2553.25    74.7 2551.13
   149.6 2549.75   230.5 2550.18   278.6 2548.28     287  2546.6   332.7 2548.01
   374.3 2547.95   395.2 2550.85   401.8 2547.11   407.6 2546.17   425.2 2546.96
   436.8 2548.26   449.2 2547.34   474.2 2547.22   549.1 2548.09   557.1 2548.78
   574.1 2552.67   707.2 2554.81   765.5 2559.31   793.1 2560.32   844.6  2563.9
     882 2568.66   898.7  2573.1   902.8 2573.59   911.2  2572.7   933.6 2574.82
#Mann= 4 ,-1,0
       0     .05       0   401.8    .045       0   425.2     .05       0
     820     .06       0
#XS Ineff= 3 ,-1
  204.51     390 2551.07     390   391.8 2547.25   435.2   933.6 2548.16
Permanent Ineff=
       F       F       F
Bank Sta=401.8,425.2
XS Rating Curve= 0 ,0
Exp/Cntr(USF)=0,0
Exp/Cntr=0.5,0.3

Type RM Length L Ch R = 1 ,2898    ,74.9,74.1,72.9
BEGIN DESCRIPTION:
structure xs 2
END DESCRIPTION:
XS GIS Cut Line= 2
2297299.86782929489673.4082652362298214.95795786489400.115452271
#Sta/Elev= 30
       0 2560.76     3.6 2560.41    25.4 2562.47    37.9 2562.57    50.4 2558.25
    71.3 2555.08    96.3 2552.66   146.4 2549.77   251.2  2548.7   313.4 2545.96
   409.4  2548.1   420.1 2546.56   426.1 2545.88   453.42546.561   460.1 2547.21
   505.4 2546.35     518 2547.41   534.7 2546.89   559.7 2547.82   572.2 2547.52
   576.4 2547.91   588.9 2551.69   595.1 2552.38   691.6  2553.7   820.1 2561.01
   856.1 2563.89   872.8 2566.38   906.9 2573.03   927.1 2575.22     955 2579.27
#Mann= 3 ,-1,0
       0     .05       0   420.1    .045       0   453.4     .05       0
#XS Ineff= 2 , 0
           412.1  2547.4   461.4          2547.4
Permanent Ineff=
       F       F
Bank Sta=420.1,453.4
XS Rating Curve= 0 ,0
Exp/Cntr(USF)=0,0
Exp/Cntr=0.5,0.3

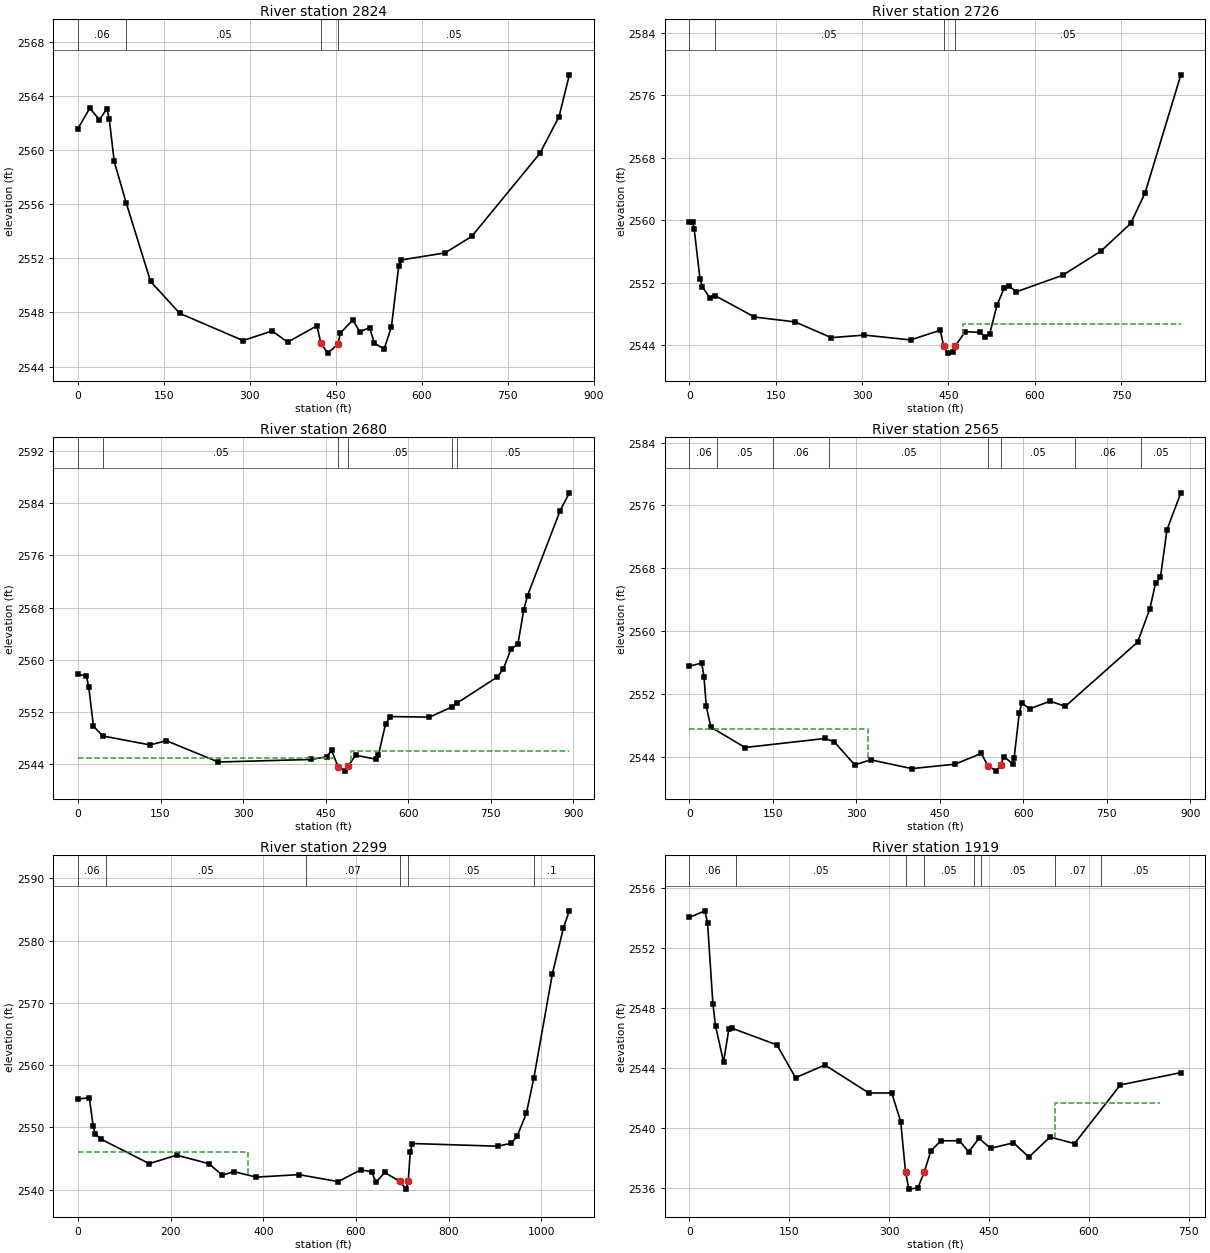
Type RM Length L Ch R = 1 ,2824    ,98.3,97.8,96.4
BEGIN DESCRIPTION:
structure xs 4
END DESCRIPTION:
XS GIS Cut Line= 2
2297324.80221921489766.4914623282298132.72672468489479.136870178
#Sta/Elev= 30
       0  2561.6    20.6 2563.11    37.5 2562.24    50.3 2563.07    54.5 2562.34
    63.2 2559.17    84.2 2556.09   126.7 2550.29   177.6 2547.93     288 2545.92
     339 2546.63   365.8  2545.8     417 2547.01   423.9 2545.71   435.8 2544.99
   453.6 2545.65   457.8 2546.47   479.7 2547.45   491.8 2546.56   508.8 2546.88
   517.3 2545.72   534.3  2545.3     547 2546.94   559.7 2551.41     564 2551.88
   640.4  2552.4   687.1 2553.62     806 2559.76   839.5 2562.48   857.5 2565.57
#Mann= 4 ,-1,0
       0     .06       0    84.2     .05       0   423.9    .045       0
   453.6     .05       0
Bank Sta=423.9,453.6
XS Rating Curve= 0 ,0
Exp/Cntr(USF)=0,0
Exp/Cntr=0.5,0.3

Type RM Length L Ch R = 1 ,2726    ,46.1,45.9,46.1
BEGIN DESCRIPTION:
structure xs 3
END DESCRIPTION:
XS GIS Cut Line= 3
2297359.15983349489874.770004298  2297824.549336489689.447115158
2298158.75522035489575.962874055
#Sta/Elev= 30
       0 2559.82     5.4 2559.77     8.2 2558.86    18.3 2552.48    22.6 2551.46
    35.5 2550.02    44.1 2550.35     113  2547.6   183.7 2546.97   246.5 2544.96
   303.8 2545.29   384.3 2544.67   435.9 2545.91   441.8 2543.85   448.9 2542.98
   457.5 2543.17   461.8 2543.89   479.3 2545.73   504.8 2545.63   513.5 2545.07
   521.7 2545.43   534.3 2549.09     547 2551.33   555.5 2551.55   568.1 2550.83
   648.4 2552.94   715.3 2556.05   766.7 2559.57     792 2563.53   853.9 2578.59
#Mann= 4 ,-1,0
       0     .06       0    44.1     .05       0   441.8    .045       0
   461.8     .05       0
#XS Ineff= 2 , 0
           428.7 2545.02   474.9         2546.65
Permanent Ineff=
       F       F
Bank Sta=441.8,461.8
XS Rating Curve= 0 ,0
Exp/Cntr(USF)=0,0
Exp/Cntr=0.5,0.3

Type RM Length L Ch R = 1 ,2680    ,116.7,114.6,113
BEGIN DESCRIPTION:
structure xs 2
END DESCRIPTION:
XS GIS Cut Line= 3
2297353.95413436 489917.456737192297884.93544594489715.475610823
 2298192.0716948489610.320488334
#Sta/Elev= 30
       0 2557.78    15.2  2557.5    19.5 2555.89    28.1  2549.8    45.2 2548.31
   130.8 2546.94   160.7 2547.58   254.9 2544.32   423.6 2544.71   451.7 2545.12
   460.8 2546.09  472.48  2543.6     486 2542.92  490.68 2543.64   504.2 2545.36
   541.4 2544.75   545.9 2545.43   558.7 2550.13   567.3 2551.29   638.6  2551.2
   678.9 2552.75     689 2553.38   761.8 2557.36   772.8  2558.6   786.6 2561.62
   799.2  2562.4   809.8 2567.63   816.7 2569.85   875.9 2582.87   892.7 2585.61
#Mann= 6 ,-1,0
       0     .06       0    45.2     .05       0  472.48    .045       0
  490.68     .05       0   678.9     .06       0     689     .05       0
#XS Ineff= 2 , 0
           466.4    2545   496.8            2546
Permanent Ineff=
       F       F
Bank Sta=472.48,490.68
XS Rating Curve= 0 ,0
Exp/Cntr(USF)=0,0
Exp/Cntr=0.5,0.3

Type RM Length L Ch R = 1 ,2565    ,257.2,266.6,286.5
XS GIS Cut Line= 3
2297342.69941283489969.2117979722297843.88330258 489854.15543573
2298164.51272358 489671.65403552
#Sta/Elev= 30
       0 2555.53      22 2555.92    26.1 2554.16    30.2 2550.41    38.5 2547.75
     100 2545.16   243.7 2546.31   260.1  2545.9     297 2542.95   325.7 2543.59
   399.6 2542.47   477.6 2543.04   524.3  2544.4536.70522542.826   551.4 2542.15
   559.1 2542.92   565.2 2544.01   580.9 2543.07   583.6 2543.87   592.8 2549.56
   597.4 2550.84   611.2 2550.08     648 2551.06   675.6 2550.41   805.5 2558.59
   827.5 2562.84   837.8  2566.1   846.6 2566.89   858.3 2572.92   883.2 2577.61
#Mann= 8 ,-1,0
       0     .06       0      50     .05       0     150     .06       0
     250     .05       0536.7052    .045       0   559.1     .05       0
  692.16     .06       0  812.16     .05       0
#XS Ineff= 2 , 0
          320.56 2547.49
Permanent Ineff=
       F       F
Bank Sta=536.7052,559.1
XS Rating Curve= 0 ,0
Exp/Cntr(USF)=0,0
Exp/Cntr=0.3,0.1

Type RM Length L Ch R = 1 ,2299    ,383.8,380.2,387.9
XS GIS Cut Line= 4
2297336.25475731490004.9124826272297718.36348508489919.070503921
2298039.02414028490104.861905984 2298336.7901307490084.039109451
#Sta/Elev= 30
       0 2554.54    24.5 2554.75    32.7 2550.24    36.8 2548.99    49.1 2548.12
   153.7 2544.16   213.1 2545.52   282.8 2544.14   311.5 2542.29   336.1 2542.87
   385.3 2541.99   476.9 2542.39   561.3 2541.27   611.1 2543.18   634.1 2542.82
   643.3 2541.13   661.9 2542.74 694.123 2541.32   708.1 2540.06 712.9232541.349
   717.3 2546.09     722 2547.39   906.1 2546.96   935.4 2547.44   947.8 2548.53
   967.9 2552.26   983.9 2557.86    1024 2574.66  1047.8 2582.03  1060.7 2584.79
#Mann= 6 ,-1,0
       0     .06       0      60     .05       0  491.28     .07       0
 694.123    .045       0 712.923     .05       0  985.21      .1       0
#XS Ineff= 2 , 0
           367.1 2545.98
Permanent Ineff=
       F       F
Bank Sta=694.123,712.923
XS Rating Curve= 0 ,0
Exp/Cntr(USF)=0,0
Exp/Cntr=0.3,0.1

Type RM Length L Ch R = 1 ,1919    ,253.6,238.8,223.2
XS GIS Cut Line= 4
2297328.96677852490036.146677426 2297605.9099724490043.434656212
2297756.25253584490255.4084779182297931.18901184490354.359449611
#Sta/Elev= 30
       0 2554.04    23.2 2554.48    27.2 2553.64    35.2 2548.27    39.2 2546.78
    51.2 2544.41    59.2  2546.6    63.2 2546.66   131.3 2545.54   159.3 2543.35
   203.3  2544.2   269.4 2542.33   303.7 2542.33   317.2 2540.43  324.42 2537.08
   329.4 2535.92     343    2536   352.7 2537.08   362.5 2538.46   377.3 2539.14
   405.4 2539.15   419.2  2538.4   434.8 2539.31   452.1 2538.64   486.5 2539.01
   509.7 2538.06   541.4 2539.39   578.2 2538.96   647.1 2542.87   737.9 2543.69
#Mann= 8 ,-1,0
       0     .06       0      70     .05       0  324.42    .045       0
   352.7     .05       0  427.04     .07       0  437.04     .05       0
  548.41     .07       0  618.41     .05       0
#XS Ineff= 1 ,-1
  548.96     706 2541.68
Permanent Ineff=
       F
Bank Sta=324.42,352.7
XS Rating Curve= 0 ,0
Exp/Cntr(USF)=0,0
Exp/Cntr=0.3,0.1

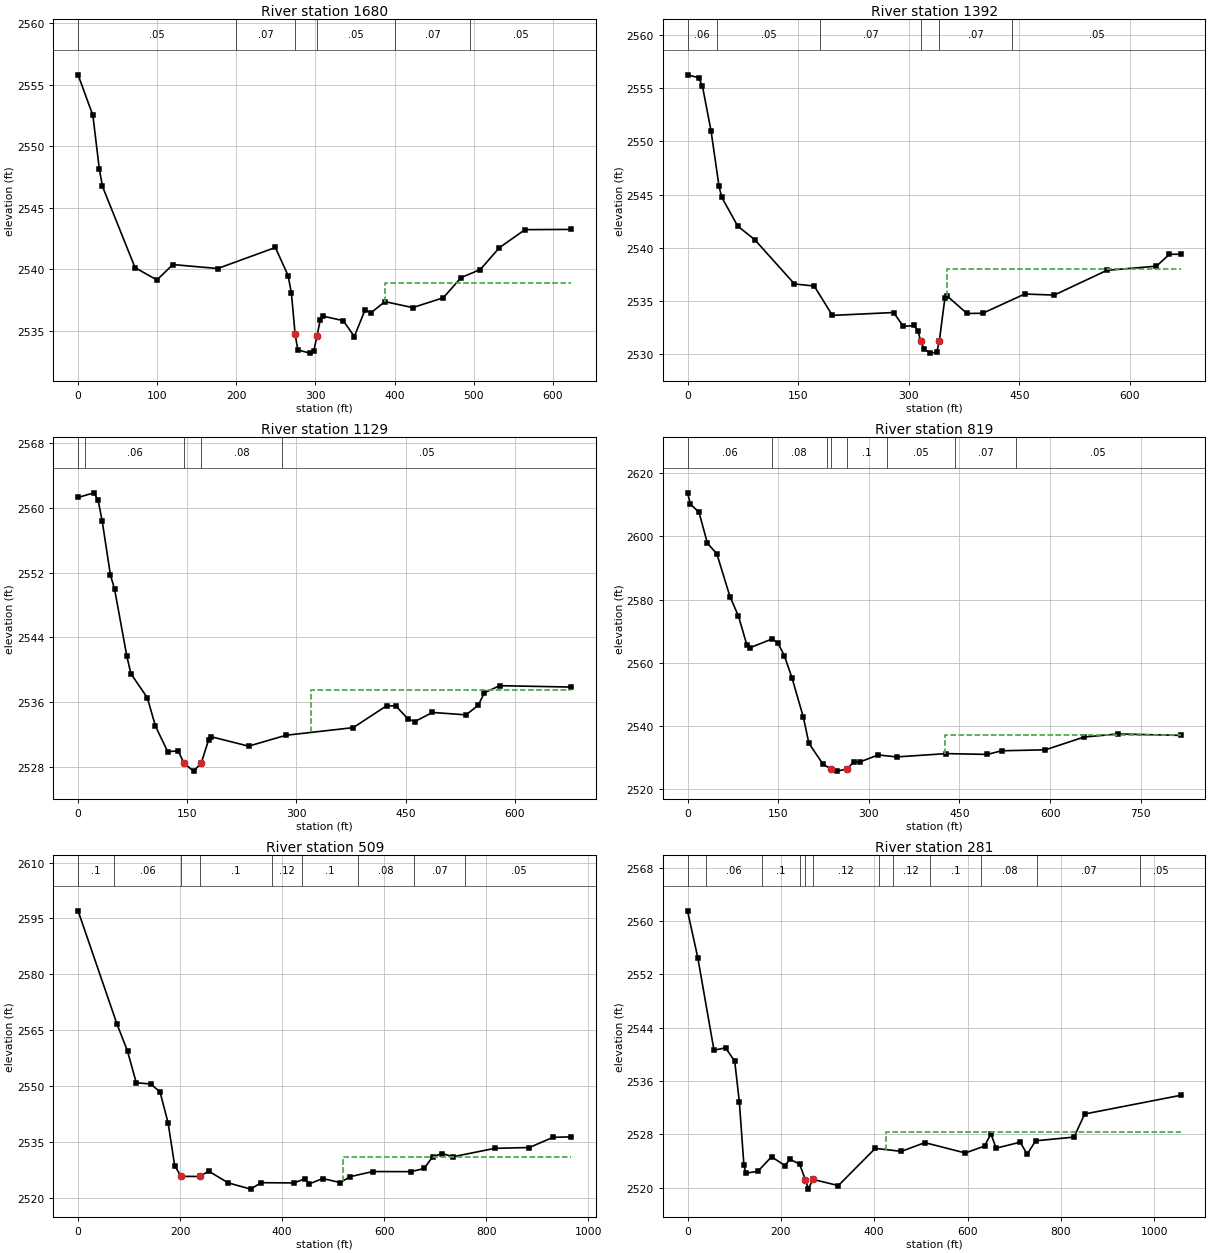
Type RM Length L Ch R = 1 ,1680    ,273.3,287.6,294.2
XS GIS Cut Line= 3
2297297.73258372490273.5265578982297738.13473039490341.200646629
2297914.03864444490366.585828646
#Sta/Elev= 30
       0 2555.81    18.7 2552.51    26.8 2548.17    30.8 2546.74      72 2540.13
    99.6 2539.13   119.8 2540.38   176.5 2540.06   249.3 2541.77   265.5 2539.47
   269.6 2538.04   274.32534.703   277.7 2533.44     293 2533.18   297.9 2533.36
   301.9 2534.57     306 2535.88     310 2536.18   335.1 2535.82   349.1 2534.53
   362.6 2536.69   370.2 2536.46   387.7 2537.37   422.8 2536.88   461.5 2537.68
     484 2539.32   508.3 2539.98   532.5 2541.76   564.8 2543.22   623.3 2543.24
#Mann= 6 ,-1,0
       0     .05       0     200     .07       0   274.3    .045       0
   301.9     .05       0     400     .07       0  495.57     .05       0
#XS Ineff= 2 , 0
                          388.45         2538.89
Permanent Ineff=
       F       F
Bank Sta=274.3,301.9
XS Rating Curve= 0 ,0
Exp/Cntr(USF)=0,0
Exp/Cntr=0.3,0.1

Type RM Length L Ch R = 1 ,1392    ,260.9,262.7,262.9
XS GIS Cut Line= 3
2297264.41610927490351.6120448952297576.75805726490632.719798086
2297776.54566498490780.781116414
#Sta/Elev= 30
       0 2556.26    15.1 2555.99    20.3 2555.18      32 2550.95    42.7 2545.79
    46.3 2544.76    68.1 2542.03    91.2 2540.75     145 2536.59   171.9 2536.39
   196.4 2533.63   279.5  2533.9   292.7 2532.59   307.3 2532.68   312.5 2532.17
   316.22531.202     321 2530.44   329.5 2530.08     338 2530.16   341.52531.228
   349.1 2535.28   352.1 2535.45     379 2533.81   400.3 2533.83   457.3 2535.64
   497.3 2535.54   568.8 2537.87     636 2538.26   653.5 2539.38   668.9 2539.38
#Mann= 6 ,-1,0
       0     .06       0      40     .05       0     180     .07       0
   316.2    .045       0   341.5     .07       0  440.21     .05       0
#XS Ineff= 2 , 0
                          351.77         2538.03
Permanent Ineff=
       F       F
Bank Sta=316.2,341.5
XS Rating Curve= 0 ,0
Exp/Cntr(USF)=0,0
Exp/Cntr=0.3,0.1

Type RM Length L Ch R = 1 ,1129    ,314,310.2,307.1
XS GIS Cut Line= 3
2297192.57746123490624.390679473 2297394.5585876490824.289526186
2297770.12442994490942.563867396
#Sta/Elev= 30
       0 2561.29    21.9 2561.86    27.6 2560.92    33.2 2558.34    44.5 2551.67
    50.1 2549.97      67 2541.66    72.6 2539.48    95.1 2536.52   106.4 2532.98
   123.2 2529.84   137.6 2529.93   145.8 2528.38   158.7 2527.43   169.22528.406
   179.5 2531.33   183.1 2531.68   234.3 2530.52   285.9 2531.87   378.1 2532.81
   424.3 2535.53   436.8 2535.49   453.6 2533.87   462.8 2533.56   487.1 2534.69
   533.3 2534.39   550.1  2535.6   558.5 2537.13   579.4    2538   677.9 2537.83
#Mann= 5 ,-1,0
       0      .1       0      10     .06       0   145.8    .045       0
   169.2     .08       0     280     .05       0
#XS Ineff= 2 , 0
                          319.44         2537.46
Permanent Ineff=
       F       F
Bank Sta=145.8,169.2
XS Rating Curve= 0 ,0
Exp/Cntr(USF)=0,0
Exp/Cntr=0.3,0.1

Type RM Length L Ch R = 1 ,819     ,307.3,309.9,312.2
XS GIS Cut Line= 3
2296999.96659331490886.7579157842297311.09316408 491073.65608233
2297764.17893598 491062.89906563
#Sta/Elev= 30
       0 2613.82     4.9 2610.18    18.9 2607.73    32.9 2597.87    48.6 2594.45
    70.2 2580.96    84.2  2574.8    98.2 2565.63   102.9  2564.7   140.2 2567.53
   149.6 2566.22   160.1 2562.27   172.9 2555.19   191.6 2542.76   200.9 2534.45
   224.2 2527.83   237.7 2526.26   247.6 2525.63   264.3 2526.35   275.6 2528.65
   284.7 2528.48   315.4 2530.76   345.9 2530.13     428 2531.18   496.1 2530.93
   520.1 2532.08   592.1 2532.38   656.1 2536.43   712.1 2537.41   816.2 2536.96
#Mann= 8 ,-1,0
       0     .06       0     140     .08       0     230      .1       0
   237.7    .045       0   264.3      .1       0     330     .05       0
  442.95     .07       0  542.95     .05       0
#XS Ineff= 2 , 0
                          426.48         2537.09
Permanent Ineff=
       F       F
Bank Sta=237.7,264.3
XS Rating Curve= 0 ,0
Exp/Cntr(USF)=0,0
Exp/Cntr=0.3,0.1

Type RM Length L Ch R = 1 ,509     ,230.2,228.5,216.3
XS GIS Cut Line= 3
2296848.78067417491116.3305258612297167.26377614491373.402087992
2297682.83507575491160.603961561
#Sta/Elev= 30
       0 2597.06    76.3 2566.64    96.9  2559.4     114 2550.92   142.4 2550.55
   160.6 2548.47   176.5 2540.11   189.4 2528.62   202.1 2525.76   238.2 2525.74
   256.2 2527.15   294.3 2524.02   338.5 2522.34   358.6 2524.07   423.3    2524
   444.9 2525.14   453.5 2523.75   479.5 2525.19   514.1 2524.09   532.7 2525.66
   577.6 2527.06   652.6 2527.03   678.6 2527.89     695 2531.03   713.9 2531.89
   734.9 2531.03     817 2533.29   884.9 2533.51   930.9 2536.25     967 2536.37
#Mann= 9 ,-1,0
       0      .1       0      70     .06       0   202.1    .045       0
   238.2      .1       0     380     .12       0  439.29      .1       0
  549.29     .08       0  659.29     .07       0  759.29     .05       0
#XS Ineff= 2 , 0
                          518.94         2530.93
Permanent Ineff=
       F       F
Bank Sta=202.1,238.2
XS Rating Curve= 0 ,0
Exp/Cntr(USF)=0,0
Exp/Cntr=0.3,0.1

Type RM Length L Ch R = 1 ,281     ,184.9,184.4,184.9
XS GIS Cut Line= 3
2296770.23103019 491311.990548152297110.13676234491557.636707519
 2297668.5533223491250.579008307
#Sta/Elev= 30
       0 2561.55    22.1 2554.48    56.7 2540.62    81.4 2540.98   101.1 2538.98
     111 2532.89   120.8 2523.37     125 2522.16   150.5 2522.42   180.1 2524.62
   208.5  2523.3   219.5 2524.24     240 2523.52   252.5 2521.18     259 2519.76
   268.4 2521.23   323.1 2520.29   402.2 2525.88   458.2 2525.43   508.4 2526.74
     595 2525.19   636.3 2526.22   649.9 2528.07   661.1 2525.91   712.8 2526.81
   727.5    2525   745.8 2527.02     828 2527.57   850.8 2531.04  1056.6 2533.85
#Mann= 12 ,-1,0
       0      .1       0      40     .06       0     160      .1       0
     240     .12       0   252.5    .045       0   268.4     .12       0
     410      .1       0  439.38     .12       0  519.38      .1       0
  629.38     .08       0  749.38     .07       0  969.38     .05       0
#XS Ineff= 2 , 0
                          425.92         2528.39
Permanent Ineff=
       F       F
Bank Sta=252.5,268.4
XS Rating Curve= 0 ,0
Exp/Cntr(USF)=0,0
Exp/Cntr=0.3,0.1

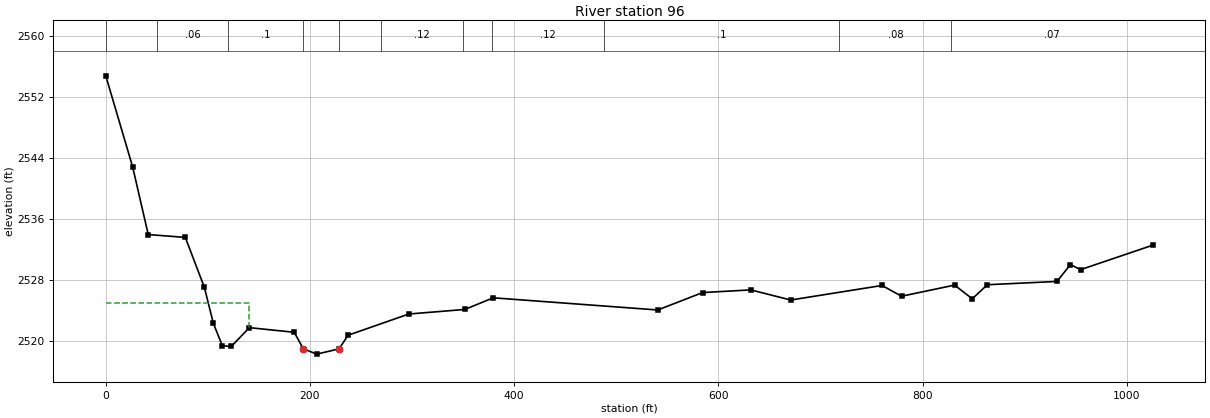
Type RM Length L Ch R = 1 ,96      ,,,
XS GIS Cut Line= 3
2296660.26152861491501.9378690582297004.45178679491659.037157027
2297565.72469745491336.269529018
#Sta/Elev= 30
       0  2554.8    26.3 2542.84    41.6 2533.94    77.9 2533.57    96.6 2526.99
   105.4 2522.26   114.2 2519.33     123 2519.24   140.6 2521.71   184.6  2521.1
   193.4 2518.94   206.6 2518.23   228.5 2518.92   237.3 2520.71   296.8  2523.5
   351.7  2524.1   379.5 2525.63   540.6 2524.03   584.6 2526.32   631.8 2526.67
   670.9 2525.34   760.3 2527.25   779.5 2525.84   831.4  2527.3   848.7  2525.5
   863.5 2527.35   931.7 2527.78   944.9    2530   954.8 2529.33  1025.8 2532.56
#Mann= 11 ,-1,0
       0      .1       0      50     .06       0     120      .1       0
   193.4    .045       0   228.5      .1       0     270     .12       0
     350      .1       0  378.35     .12       0  488.35      .1       0
  718.35     .08       0  828.35     .07       0
#XS Ineff= 2 , 0
          140.62 2524.95
Permanent Ineff=
       F       F
Bank Sta=193.4,228.5
XS Rating Curve= 0 ,0
Exp/Cntr(USF)=0,0
Exp/Cntr=0.3,0.1
LCMann Table=0

Chan Stop Cuts=-1
Use User Specified Reach Order=0
Composite Channel Slope=5